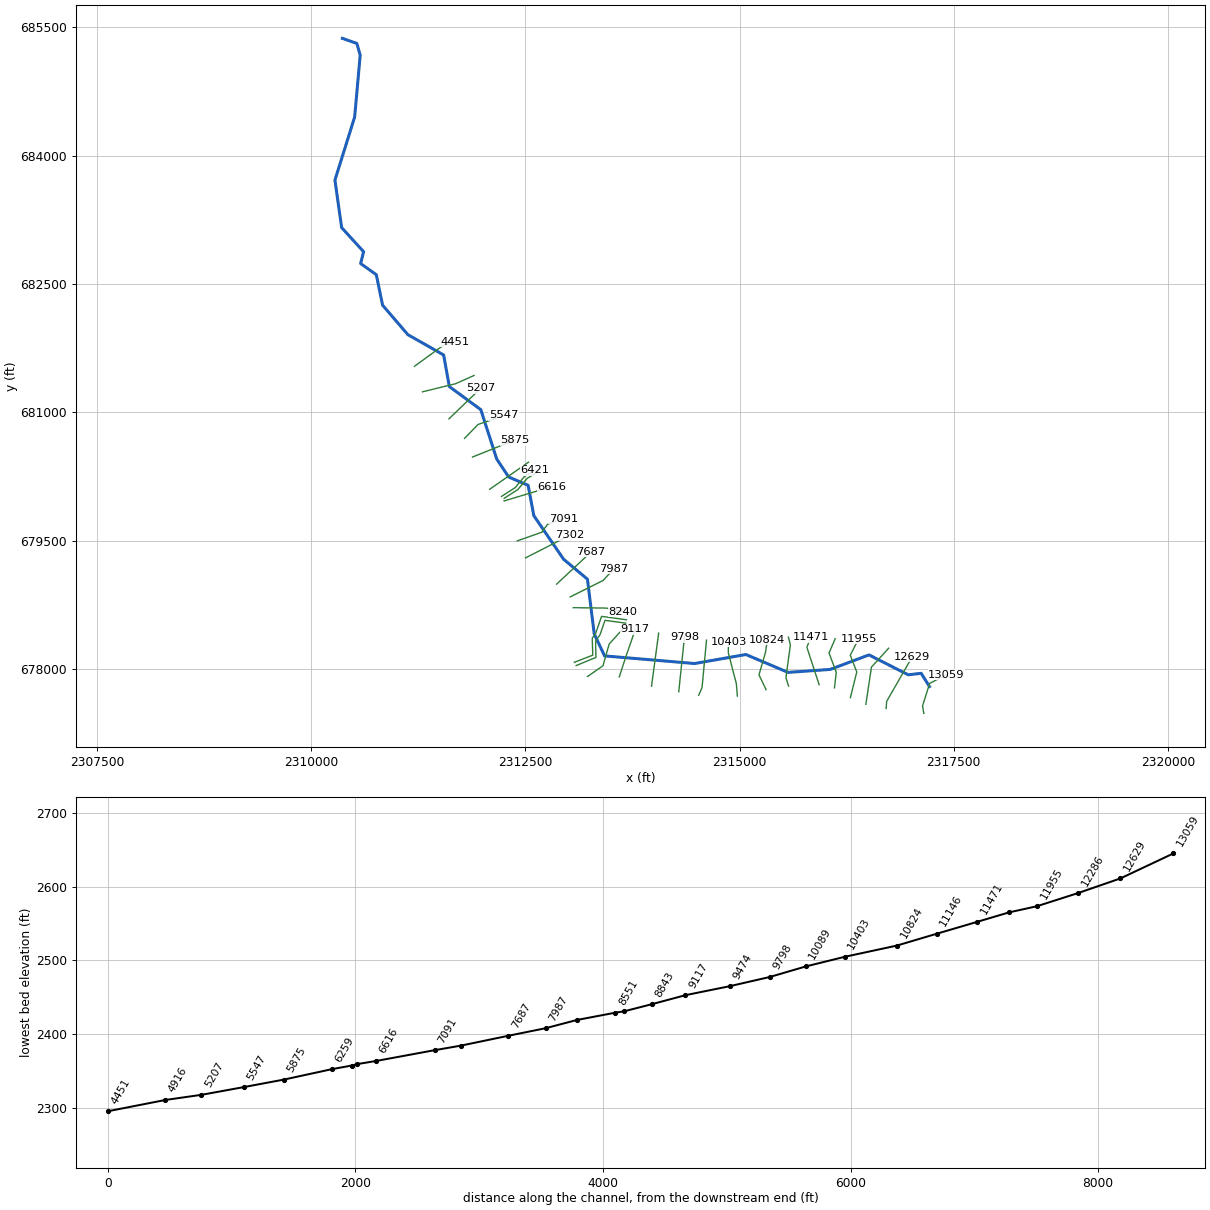
--- RFKCHENOCK.prj (project) ---

Proj Title=RFKCHENOCK
Current Plan=p01
Default Exp/Contr=0,0
English Units
Geom File=g01
Flow File=f01
Plan File=p01
BEGIN DESCRIPTION:
----------MODEL BY WSP USA 2022----------
AFH study
Randolph County, WV
HEC-RAS Version: RAS 6.2
Vertical Datum: NAVD88
Projection: NAD 1983 StatePlane West Virginia S FIPS 4702 (US Feet)
Terrain: 1-meter LIDAR (FEMA Region III 3DEP collected 2016-2018)
Land Use: 2019 NLCD
Hydrologic Method:
WV SIR2010-5033 regression equations
Additional Model Notes:
None
END DESCRIPTION:
DSS Export Rating Curves= 0
DSS Export Rating Curve Sorted= 0
DSS Export Volume Flow Curves= 0
DXF OffsetX= 0
DXF OffsetY= 0
DXF ScaleX= 0
DXF ScaleY= 0

--- RFKCHENOCK.p01 (plan) ---

Plan Title=Floodplain
Program Version=6.20
Short Identifier=Floodplain
Geom File=g01
Flow File=f01
Subcritical Flow
K Sum by GR= 0
Std Step Tol= 0.01
Critical Tol= 0.01
Num of Std Step Trials= 20
Max Error Tol= 0.3
Flow Tol Ratio= 0.001
Split Flow NTrial= 30
Split Flow Tol= 0.02
Split Flow Ratio= 0.02
Log Output Level= 0
Friction Slope Method= 1
Unsteady Friction Slope Method= 2
Unsteady Bridges Friction Slope Method= 1
Parabolic Critical Depth
Global Vel Dist= 0 , 0 , 0
Global Log Level= 0
CheckData=True
Encroach Param=-1 ,0,0, 0
Mapping Interval=1HOUR
Computation Time Step Use Courant=        0
Computation Time Step Use Time Series=    0
Computation Time Step Count To Double=0
Computation Time Step Max Doubling=0
Computation Time Step Max Halving=0
Computation Time Step Residence Courant=0
Run HTab= 0
Run UNet= 0
Run Sediment= 0
Run PostProcess= 0
Run WQNet= 0
Run RASMapper=-1
UNET Theta= 0
UNET Theta Warmup= 0
UNET ZTol= 0
UNET ZSATol= 0
UNET MxIter= 0
UNET Max Iter WO Improvement= 0
UNET MaxInSteps= 0
UNET DtIC= 0
UNET DtMin= 0
UNET MaxCRTS= 0
UNET WFStab= 0
UNET SFStab= 0
UNET WFX= 1
UNET SFX= 1
UNET Gravity=32.174
UNET 1D Methodology=Finite Difference
UNET DSS MLevel= 1
UNET Pardiso=0
UNET DZMax Abort= 0
UNET Use Existing IB Tables= 0
UNET Froude Reduction=False
UNET Froude Limit= 0
UNET Froude Power= 0
UNET D1 Cores= 0
UNET WindReference=Eulerian
UNET WindDragFormulation=Hsu (1988)
UNET D2 Coriolis=0
UNET D2 Cores= 0
UNET D2 Theta= 1
UNET D2 Theta Warmup= 1
UNET D2 Z Tol= 0.01
UNET D2 Volume Tol= 0.01
UNET D2 Max Iterations= 20
UNET D2 Equation= 0
UNET D2 RampUpFraction=0.1
UNET D2 TimeSlices= 1
UNET D2 Turbulence Formulation=Non-Conservative (original)
UNET D2 Eddy Viscosity=0.3
UNET D2 Transverse Eddy Viscosity=0.1
UNET D2 Smagorinsky Mixing=0
UNET D2 BCVolumeCheck=0
UNET D2 Cores=0
UNET D2 SolverType=PARDISO (Direct)
UNET D2 Minimum Iterations= 2147483647
UNET D2 Maximum Iterations= 2147483647
UNET D2 Restart Number= 10
UNET D2 Relaxation Coeff=1.3
UNET D2 SOR Precondition Iterations= 10
UNET D2 ILUT Maximum Fill= 8
UNET D2 ILUT Tolerance=1E-08
UNET D1D2 MaxIter= 0
UNET D1D2 ZTol=0.01
UNET D1D2 QTol=0.1
UNET D1D2 MinQTol=1
Write IC File= 0
Write IC File at Fixed DateTime=0
Write IC File at Sim End=0
Echo Input=False
Echo Parameters=False
Echo Output=False
Write Detailed= 0
HDF Write Warmup=0
HDF Write Time Slices=0
HDF Flush=0
HDF Compression= 1
HDF Chunk Size= 1
HDF Spatial Parts= 1
HDF Use Max Rows=0
HDF Fixed Rows= 1
Calibration Method= 0
Calibration Iterations= 20
Calibration Max Change=0.05
Calibration Tolerance=0.2
Calibration Maximum=1.5
Calibration Minimum=0.5
Calibration Optimization Method= 1
WQ AD Non Conservative
WQ ULTIMATE=-1
WQ Max Comp Step=1HOUR
WQ Output Interval=15MIN
WQ Output Selected Increments= 0
WQ Output face flow=0
WQ Output face velocity=0
WQ Output face area=0
WQ Output face dispersion=0
WQ Output cell volume=0
WQ Output cell surface area=0
WQ Output cell continuity=0
WQ Output cumulative cell continuity=0
WQ Output face conc=0
WQ Output face dconc_dx=0
WQ Output face courant=0
WQ Output face peclet=0
WQ Output face adv mass=0
WQ Output face disp mass=0
WQ Output cell mass=0
WQ Output cell source sink temp=0
WQ Output nsm pathways=0
WQ Output nsm derived pathways=0
WQ Create Restart=0
WQ Fixed Restart=0
WQ System Summary=0
WQ Write To DSS=0
Sorting and Armoring Iterations= 10
XS Update Threshold= 0.02
Bed Roughness Predictor= 0
Hydraulics Update Threshold= 0.02
Energy Slope Method= 1
Volume Change Method= 1
Sediment Retention Method= 0
Sediment TS Multiplier= 1
Warm Up Method= 0
XS Weighting Method= 0
Number of US Weighted Cross Sections= 1
Number of DS Weighted Cross Sections= 1
Upstream XS Weight=0
Main XS Weight=1
Downstream XS Weight=0
Number of DS XS's Weighted with US Boundary= 1
Upstream Boundary Weight= 1
Weight of XSs Associated with US Boundary= 0
Number of US XS's Weighted with DS Boundary= 1
Downstream Boundary Weight= 0.5
Weight of XSs Associated with DS Boundary= 0.5
Percentile Method= 0
Sediment Output Level= 3
Mass or Volume Output= 0
Output Increment Type= 1
Profile and TS Output Increment= 1
Transport Output Increment 1
XS Output Flag= 0
XS Output Increment= 10
Read HDF5 Sediment Hotstart= 0
Sediment Hotstart Type= 0
Write Gradation File= 0
Read Gradation Hotstart= 0
Write HDF5 File= 1
Write Binary Output= 1
Write DSS Sediment File= 0
DSS Sediment Output Type= 1
SV Curve= 0
Specific Gage Flag= 0
Subcell Erosion Methods= 0
Subcell Deposition Methods= 0
Advection Scheme= 1
Matrix Solver= 0
Implicit Weighting Factor= 1
Maximum Outer Loop Convergence Iterations= 5
Convergence Maximum Absolute= 0.001
Convergence RMSE= 0.0001
Grain Fractions Max Abs Error= 0.001
Max Subgrid Regions= 1
Max Subgrid Length Scale= 3.402823E+38
Initial Layer Thickness= 3.402823E+38
Min Layer Thickness= 3.402823E+38
Max Layer Thickness= 3.402823E+38
Number of Layers= 5

--- RFKCHENOCK.f01 (steady flow) ---

Flow Title=Flow
Program Version=6.20
Number of Profiles= 1
Profile Names=P100yr
River Rch & RM=RFKCHENOCK,Main,13059
     381
River Rch & RM=RFKCHENOCK,Main,9117
     440
River Rch & RM=RFKCHENOCK,Main,8240
     541
River Rch & RM=RFKCHENOCK,Main,5207
     614
River Rch & RM=RFKCHENOCK,Main,4001
     685
Boundary for River Rch & Prof#=RFKCHENOCK,Main            , 1
Up Type= 0
Dn Type= 3
Dn Slope=0.031896
DSS Import GetInterval= 0
DSS Import GetPeak= 0
DSS Import FillOption= 0

--- RFKCHENOCK.g01 (geometry) ---

Geom Title=Geometry
Program Version=6.20

River Reach=RFKCHENOCK      ,Main
Reach XY= 30
     2317215.695      677799.852     2317119.124      677953.932
     2316968.299      677936.571     2316510.399      678168.776
     2316059.011      677999.505     2315565.998      677964.652
      2315073.29      678173.506     2314474.853      678068.298
     2313424.505      678157.187     2313303.672      678414.131
     2313224.505      679053.715     2312946.033      679286.354
     2312598.811      679795.381     2312532.542      680149.472
     2312305.371      680246.439      2312166.01      680456.281
     2311980.083      681033.099     2311612.914      681302.298
     2311546.539      681671.309     2311129.699      681908.404
     2310833.908      682253.085     2310760.801      682608.585
     2310577.685      682739.654 2310612.7150251 682877.15797316
     2310356.157      683158.681     2310278.045      683713.397
     2310508.084      684450.001     2310572.671      685172.225
      2310534.16      685309.011     2310364.445      685369.022

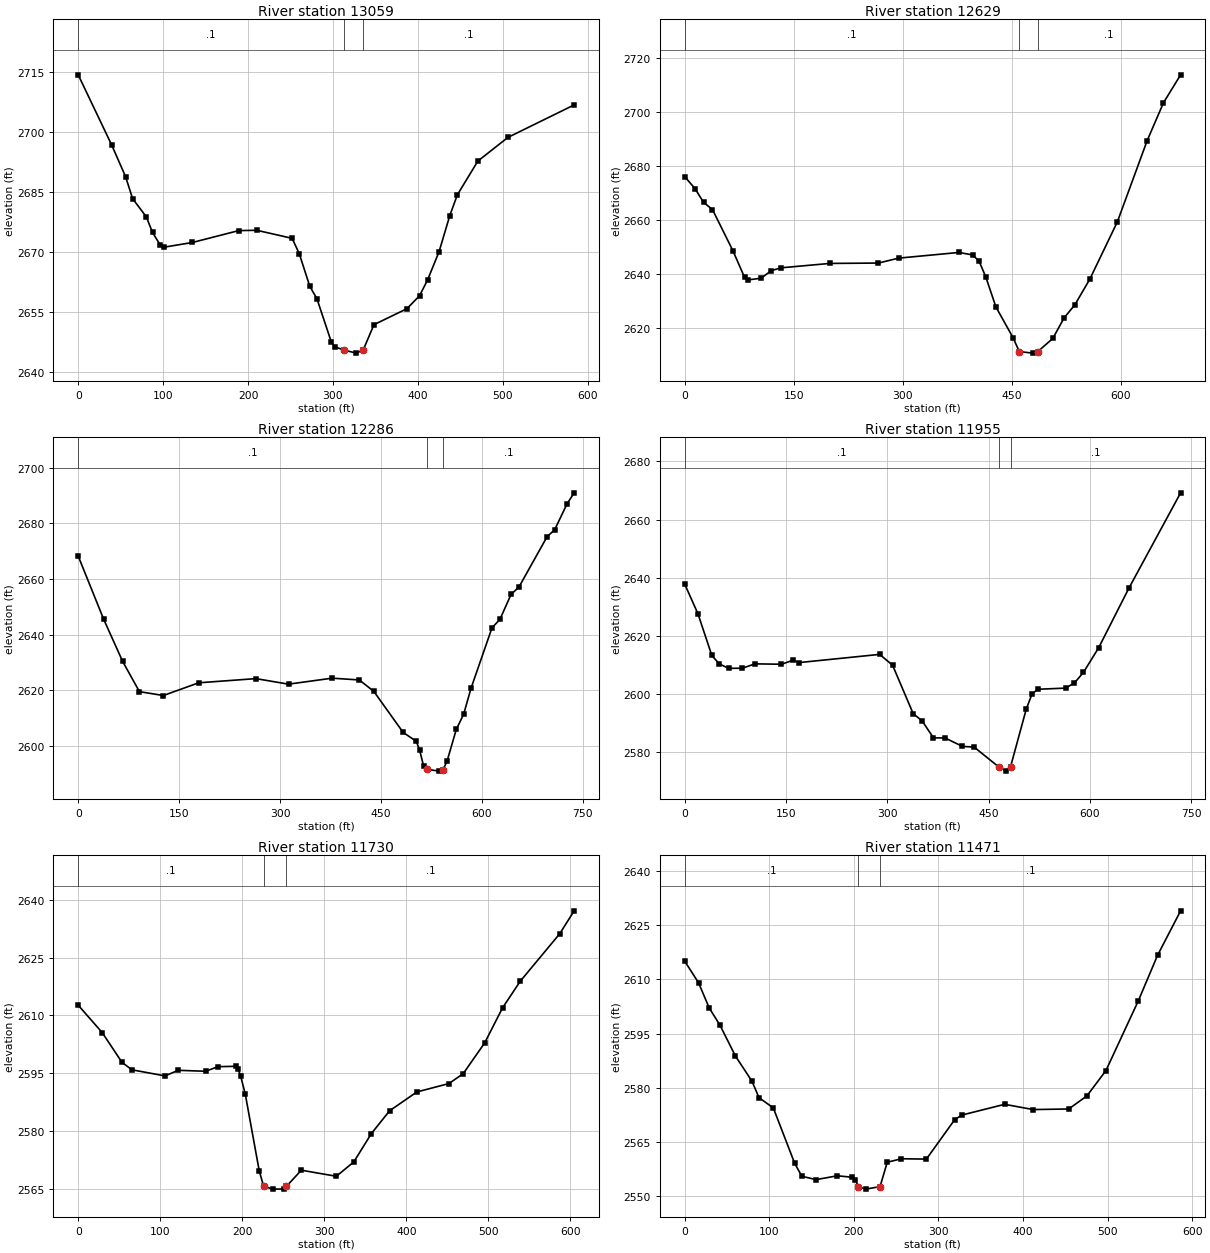
Type RM Length L Ch R = 1 ,13059   ,428.7,429.4,424.8
XS GIS Cut Line= 4
2317149.66090808677486.1284892872317135.00487378677572.436246817
 2317218.0557348677836.2448641752317413.46952544677937.208656004
#Sta/Elev= 30
       0 2714.36    39.6 2696.74    55.8 2688.91      64 2683.44    80.2 2678.87
    87.5 2674.97    96.7 2671.79   100.9 2671.28   134.5 2672.46     189 2675.43
   210.3 2675.51   251.9  2673.5   260.3 2669.69   272.8 2661.47   281.2 2658.38
     298 2647.65   302.2 2646.38  313.192645.574   327.4 2644.81   335.7 2645.61
   348.3 2651.92   387.2 2655.92     402 2659.15   411.5 2663.11     425 2670.16
   437.6 2679.16   446.5 2684.36   470.7 2692.81   506.1 2698.72   584.1 2706.84
#Mann= 3 ,-1,0
       0      .1       0  313.19    .045       0   335.7      .1       0
Bank Sta=313.19,335.7
XS Rating Curve= 0 ,0
Exp/Cntr(USF)=0,0
Exp/Cntr=0.3,0.1

Type RM Length L Ch R = 1 ,12629   ,344.7,343.1,339.8
XS GIS Cut Line= 3
2316709.97987915677543.1241782222316716.49367217677626.175039242
2317014.49970289678145.650032681
#Sta/Elev= 30
       0 2676.18    14.1 2671.76    26.1  2666.6    38.2    2664    66.3 2648.79
    82.3 2638.94    86.8 2637.96   105.2 2638.59     119 2641.38   132.2 2642.43
   199.6 2644.06   266.6  2644.2   294.3 2646.02   377.3 2648.12   396.2  2647.2
     405 2644.87   414.2 2639.06   428.1 2627.98   451.6 2616.65   460.3 2611.46
   478.7 2610.89  485.452611.393   506.4 2616.32   521.9 2623.92   536.6 2628.72
   557.1 2638.14   595.2 2659.45   636.2  2689.5   658.6 2703.46   682.2 2713.81
#Mann= 3 ,-1,0
       0      .1       0   460.3    .045       0  485.45      .1       0
Bank Sta=460.3,485.45
XS Rating Curve= 0 ,0
Exp/Cntr(USF)=0,0
Exp/Cntr=0.3,0.1

Type RM Length L Ch R = 1 ,12286   ,316.9,331,340.8
XS GIS Cut Line= 3
2316473.85488213677591.9776258812316538.99281234678026.773310045
2316739.29194774 678246.61382451
#Sta/Elev= 30
       0 2668.24    37.6  2645.7    65.9 2630.49      91 2619.56   126.6 2618.17
     179 2622.74   264.1 2624.24   312.6 2622.25   377.4  2624.4   417.8 2623.76
   439.3 2619.67     483  2604.9   502.4 2601.76   507.3 2598.66   513.2    2593
   518.7 2591.66   536.4 2591.02   542.4  2591.6   548.3 2594.69     562 2606.05
   572.8 2611.39   583.9 2620.82   614.9 2642.42   626.9 2645.58   643.3 2654.46
   655.2 2657.19     697 2675.26   708.1 2677.67   726.5    2687   737.1 2690.96
#Mann= 3 ,-1,0
       0      .1       0   518.7    .045       0   542.4      .1       0
Bank Sta=518.7,542.4
XS Rating Curve= 0 ,0
Exp/Cntr(USF)=0,0
Exp/Cntr=0.3,0.1

Type RM Length L Ch R = 1 ,11955   ,226.7,225.6,225
XS GIS Cut Line= 4
2316293.09712579677670.1431421352316368.00574554 677969.77762111
2316291.46867754678165.1914117452316389.17557286 678357.34830587
#Sta/Elev= 30
       0 2637.76    19.6 2627.54    40.2 2613.14    51.2 2610.25      65  2608.7
    85.6 2608.75     104 2610.25   143.3 2610.11   160.1 2611.46     170  2610.7
   288.7 2613.51   307.8 2609.79   338.3 2593.09   351.5  2590.6   368.4 2584.73
   385.5 2584.71   411.3 2581.79   428.5 2581.57   465.7 2574.59   475.8 2573.27
  482.472574.759   505.8 2594.69   514.4 2599.93   523.2 2601.49   563.9 2601.89
     577 2603.64   590.5 2607.33   612.9 2615.78   657.8 2636.37   734.3  2669.2
#Mann= 3 ,-1,0
       0      .1       0   465.7    .045       0  482.47      .1       0
Bank Sta=465.7,482.47
XS Rating Curve= 0 ,0
Exp/Cntr(USF)=0,0
Exp/Cntr=0.3,0.1

Type RM Length L Ch R = 1 ,11730   ,261.1,259.1,259.4
XS GIS Cut Line= 4
2316107.45402469677784.1345200062316128.62385201677964.892276344
2316043.94454273 678191.246583832316115.59626597 678357.34830587
#Sta/Elev= 30
       0 2612.65    29.2 2605.56    53.4 2597.82    65.5 2595.89   105.8 2594.31
   121.9 2595.76   155.5 2595.51   170.2  2596.7   191.9  2596.8   195.1 2596.03
   198.1  2594.2   203.7 2589.55   220.7 2569.65   226.1 2565.65   237.8 2564.94
   250.6 2564.97  253.74 2565.64     272 2569.85   314.7 2568.27     336 2572.01
   357.4 2579.35   379.6 2585.26   412.9 2590.15   451.9 2592.32   469.3 2594.88
   495.5 2602.86   517.3 2611.96     539  2618.9     587 2631.18   604.6 2637.13
#Mann= 3 ,0,0
       0      .1       0   226.1    .045       0  253.74      .1       0
Bank Sta=226.1,253.74
XS Rating Curve= 0 ,0
Exp/Cntr(USF)=0,0
Exp/Cntr=0.3,0.1

Type RM Length L Ch R = 1 ,11471   ,328.6,325.1,317.5
XS GIS Cut Line= 3
2315928.32471661677821.5888298772315785.02127014678259.641410552
 2315833.8747178678375.261236678
#Sta/Elev= 30
       0 2615.07    16.4 2609.09      29 2602.13    41.7 2597.37      60 2588.83
    79.5  2581.9    87.9 2577.31   104.8 2574.49     130  2559.2   138.5  2555.6
   155.2 2554.65   180.6 2555.72   197.4 2555.33   201.6 2554.63   205.5 2552.71
   214.2 2552.03     231 2552.73   239.5 2559.46   256.3 2560.43   285.8 2560.33
   319.4 2571.28   327.8 2572.51   378.3 2575.48     412 2574.03   454.1 2574.19
   475.6 2577.81   498.1 2584.81   536.4 2604.11   559.1 2616.67   586.4 2628.98
#Mann= 3 ,-1,0
       0      .1       0   205.5    .045       0     231      .1       0
Bank Sta=205.5,231
XS Rating Curve= 0 ,0
Exp/Cntr(USF)=0,0
Exp/Cntr=0.3,0.1

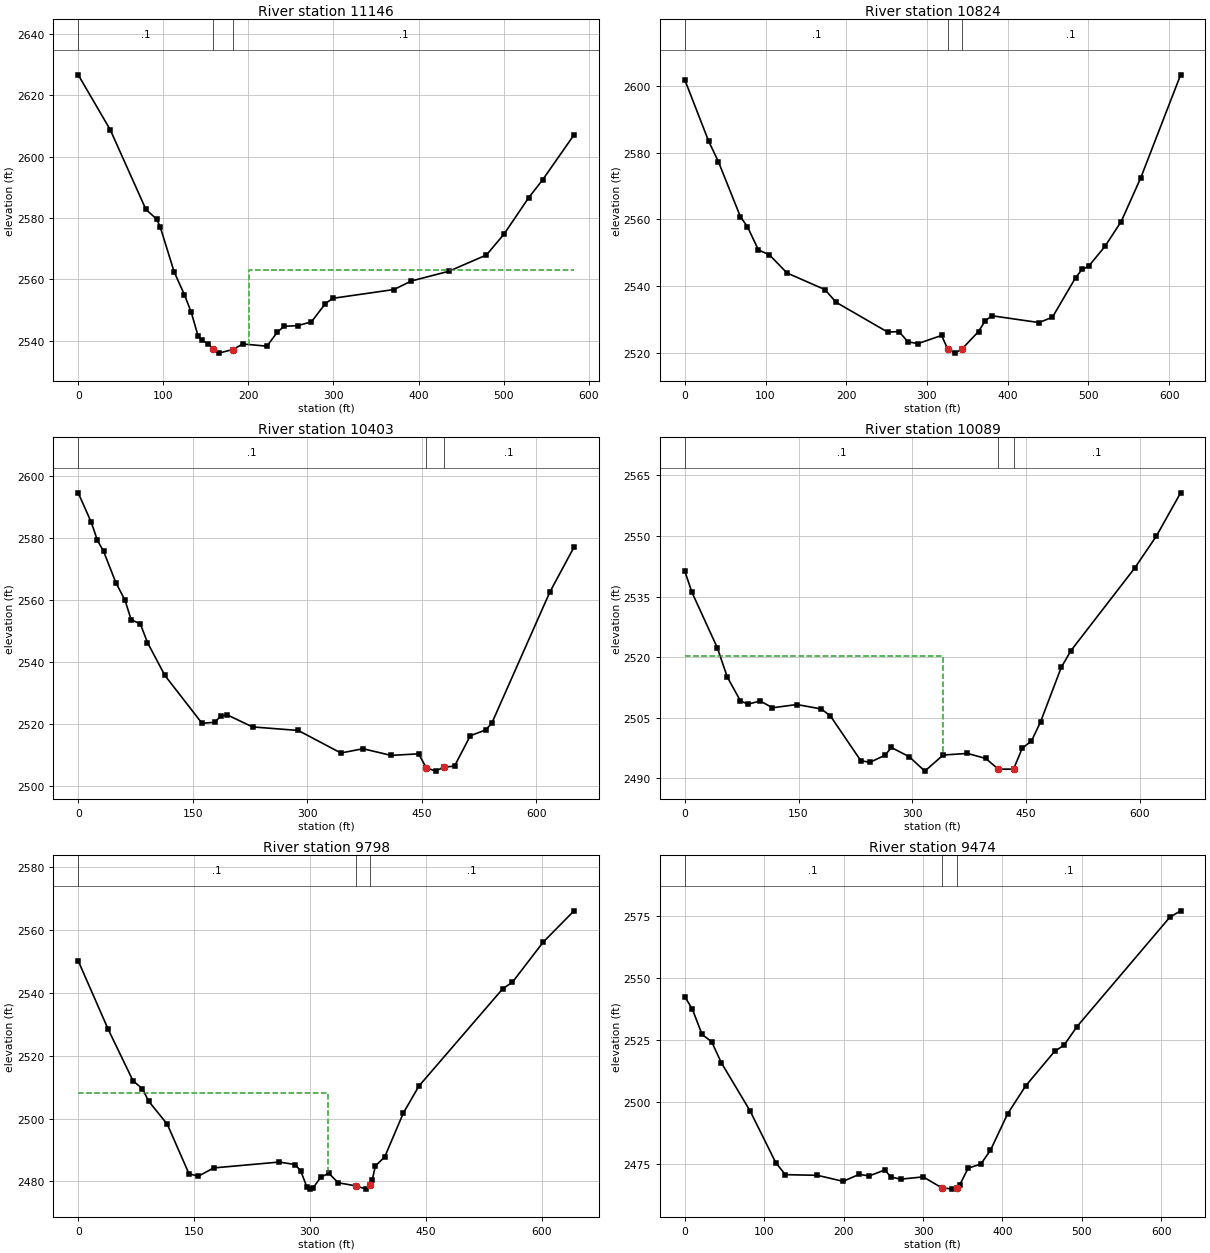
Type RM Length L Ch R = 1 ,11146   ,321.1,321.3,317.3
XS GIS Cut Line= 4
 2315571.6945487677805.3043473252315540.75403185677903.011242642
2315592.86437602678284.0681343822315570.06610044678376.889684933
#Sta/Elev= 30
       0 2626.61    37.6 2608.75    79.6 2582.79    92.2 2579.64    96.4 2577.09
   112.8 2562.44   124.9    2555   132.9 2549.27     141  2541.5     145  2540.2
   153.1 2539.07   158.62537.239   165.2 2536.03   181.4 2537.18   193.5 2539.01
   221.8 2538.29   233.9  2542.8   241.9 2544.76   258.1 2544.98   274.1 2546.21
   290.4 2552.13   299.2 2553.87   371.1 2556.73   391.6 2559.52   435.7 2562.68
   479.8 2567.98   500.6 2574.83   529.4 2586.62   545.9 2592.47   582.7 2607.08
#Mann= 3 ,-1,0
       0      .1       0   158.6    .045       0   181.4      .1       0
#XS Ineff= 2 , 0
                          201.01         2563.24
Permanent Ineff=
       F       F
Bank Sta=158.6,181.4
XS Rating Curve= 0 ,0
Exp/Cntr(USF)=0,0
Exp/Cntr=0.3,0.1

Type RM Length L Ch R = 1 ,10824   ,412.5,421.7,424.8
XS GIS Cut Line= 4
2315309.51437959677762.9646926872315226.46351857677935.580207748
2315303.00058657678201.0172733612315324.17041389678345.949168083
#Sta/Elev= 30
       0 2601.76    29.6 2583.38    41.6  2577.3      69 2560.76    77.6 2557.85
    91.2 2550.88   104.6 2549.47   126.7 2543.99   173.5 2539.04   187.6 2535.21
   251.5  2526.3   265.3 2526.49   276.5 2523.39     289 2522.89   318.1 2525.31
   325.9 2521.17   334.8 2520.03   343.1 2521.18   363.9 2526.49   372.2 2529.71
   380.6  2531.2   438.8 2529.17   455.5 2530.78   484.1 2542.57   492.2 2545.06
   500.3    2546   520.5 2551.94   540.7 2559.39     565 2572.51   614.3 2603.26
#Mann= 3 ,-1,0
       0      .1       0   325.9    .045       0   343.1      .1       0
Bank Sta=325.9,343.1
XS Rating Curve= 0 ,0
Exp/Cntr(USF)=0,0
Exp/Cntr=0.3,0.1

Type RM Length L Ch R = 1 ,10403   ,317,314.1,309.7
XS GIS Cut Line= 4
  2314974.054039677688.0560729432314962.65490122677831.359519409
2314868.20490241 678194.503480342314871.46179892678324.779340764
#Sta/Elev= 30
       0 2594.46    17.2 2584.91    25.2 2579.11    33.2 2575.62    49.3 2565.53
    61.3 2559.86    69.3  2553.6    81.4 2552.23    90.7 2546.24   113.5 2535.64
   162.2 2520.21   178.7 2520.57     187 2522.59   195.2 2522.93   228.3 2519.06
   288.1 2517.92     344 2510.66     373 2512.03   409.7 2509.89   445.8 2510.39
   455.6 2505.97   455.6 2505.96     468 2504.82   478.6 2506.09   492.8 2506.44
   513.5 2516.22   533.7  2518.1   541.7 2520.32   617.7 2562.53   649.3 2576.97
#Mann= 3 ,-1,0
       0      .1       0   455.6    .045       0   478.6      .1       0
Bank Sta=455.6,478.6
XS Rating Curve= 0 ,0
Exp/Cntr(USF)=0,0
Exp/Cntr=0.3,0.1

Type RM Length L Ch R = 1 ,10089   ,289.4,290.2,289.3
XS GIS Cut Line= 3
2314522.97387229677697.8267624752314562.05663041677787.391416516
2314614.16697458678341.063823317
#Sta/Elev= 30
       0 2541.27     9.5 2536.02    42.9 2522.32      56  2515.1    73.3 2509.21
      83 2508.37    99.5 2509.15   115.6 2507.48   147.7 2508.28   179.9 2507.19
   191.9 2505.48   232.1 2494.38   244.2 2493.98   264.2 2495.76   272.3 2497.65
   295.9 2495.37   316.5  2491.8   340.6 2495.78   372.7 2496.18   396.8 2494.94
   413.4 2492.29  433.512492.296     445 2497.51   457.1 2499.23   469.1    2504
   496.5 2517.52   509.3 2521.65   593.4  2542.1   621.8 2549.96   653.8 2560.68
#Mann= 3 ,-1,0
       0      .1       0   413.4    .045       0  433.51      .1       0
#XS Ineff= 2 , 0
          340.14 2520.21
Permanent Ineff=
       F       F
Bank Sta=413.4,433.51
XS Rating Curve= 0 ,0
Exp/Cntr(USF)=0,0
Exp/Cntr=0.3,0.1

Type RM Length L Ch R = 1 ,9798    ,324.5,324.8,324.1
XS GIS Cut Line= 2
2314290.10577178677738.5379688572314356.87215025678376.889684933
#Sta/Elev= 30
       0 2550.24    38.9 2528.39      71 2512.01    83.1 2509.52    91.1 2505.57
   115.3 2498.22   143.4 2482.43   155.5 2481.67   175.4  2484.3   260.1 2486.17
     281 2485.37   288.3  2483.2   296.2 2478.07   300.3 2477.67   304.3 2478.02
   313.8  2481.3   324.4 2482.62   336.5 2479.57   359.62478.588   372.7 2477.55
   377.9 2478.73   380.7 2480.59   384.7 2484.92   396.8 2487.84   420.9 2501.79
     441 2510.36   549.6 2541.37   562.1 2543.44   601.9  2556.2   641.8 2566.16
#Mann= 3 ,-1,0
       0      .1       0   359.6    .045       0   377.9      .1       0
#XS Ineff= 2 , 0
          323.97    2508
Permanent Ineff=
       F       F
Bank Sta=359.6,377.9
XS Rating Curve= 0 ,0
Exp/Cntr(USF)=0,0
Exp/Cntr=0.3,0.1

Type RM Length L Ch R = 1 ,9474    ,357.8,357,356.1
XS GIS Cut Line= 2
  2313972.558362677803.6758990692314055.60922302678422.486236082
#Sta/Elev= 30
       0 2542.66     9.6 2537.52    21.7 2527.42    33.8 2524.46    45.9 2516.05
    82.2 2496.59   114.5 2475.75   126.6 2470.88     167 2470.62   199.3 2468.19
   219.5 2470.98   232.3 2470.39   251.7 2472.74   259.8 2469.91   271.9 2469.07
   300.2 2469.98  323.292465.648   336.5 2465.05   342.6 2465.64   346.2 2466.73
   356.8  2473.5   372.8 2475.16   384.9 2480.69   406.6 2495.45   429.3 2506.69
   465.6 2520.55   477.7 2523.13   493.9 2530.58   610.9 2574.69   624.4 2577.24
#Mann= 3 ,-1,0
       0      .1       0  323.29    .045       0   342.6      .1       0
Bank Sta=323.29,342.6
XS Rating Curve= 0 ,0
Exp/Cntr(USF)=0,0
Exp/Cntr=0.3,0.1

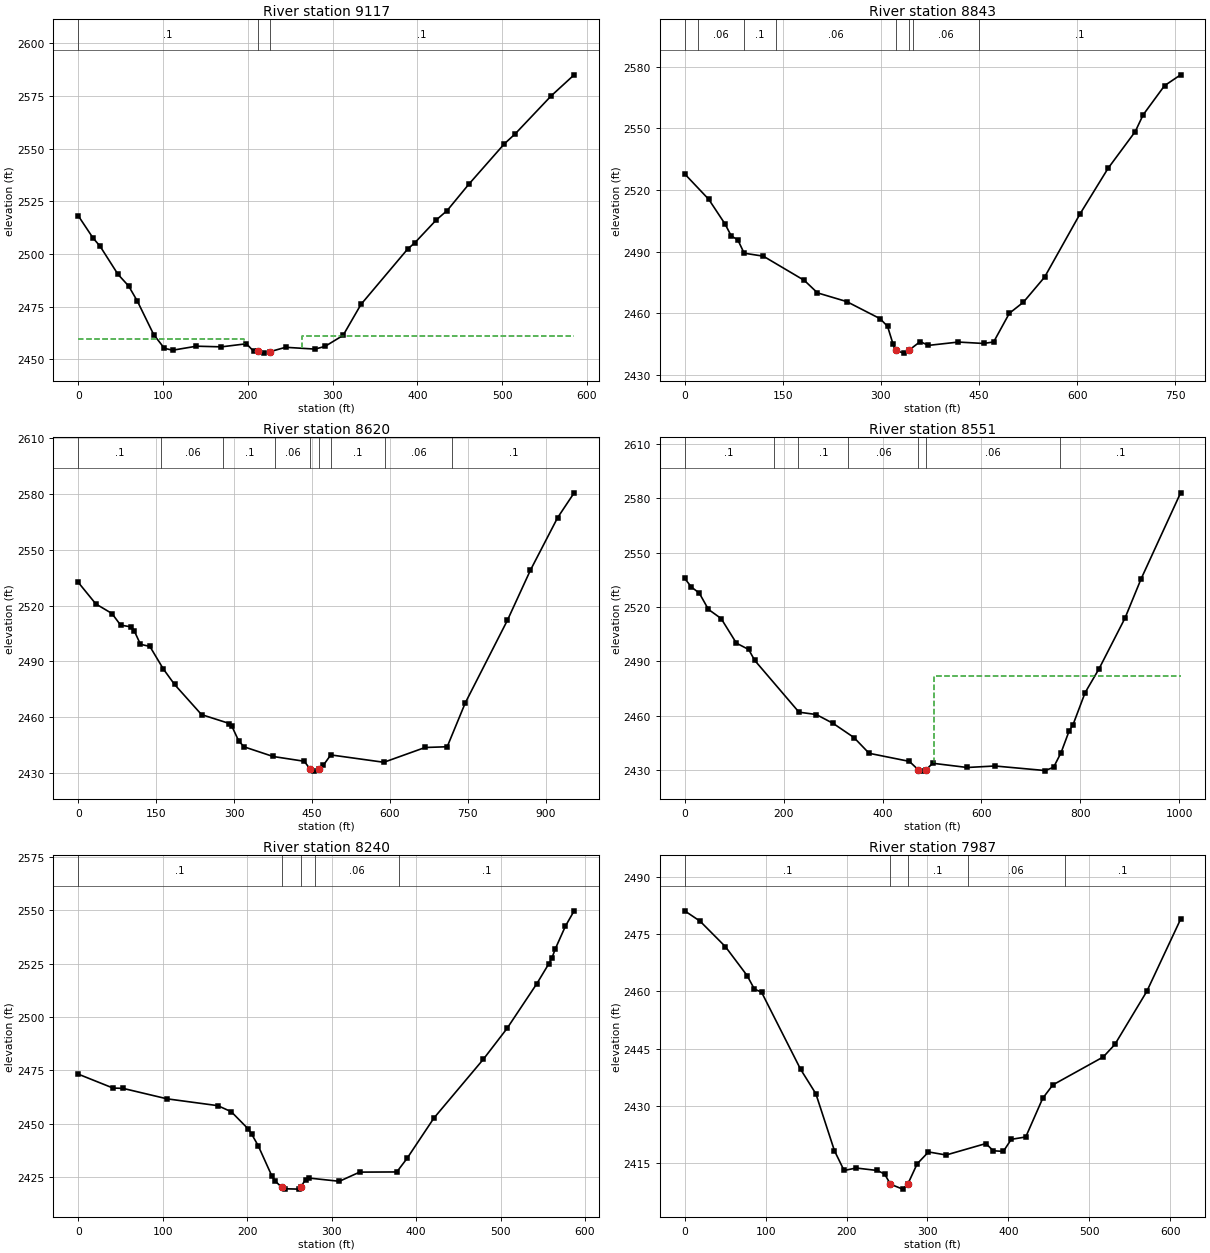
Type RM Length L Ch R = 1 ,9117    ,272.2,273.5,271
XS GIS Cut Line= 3
2313596.24291083677912.6026057372313674.21251862 678151.20839345
2313783.18209096678466.844396094
#Sta/Elev= 30
       0 2518.14    17.4  2507.6    25.9 2503.58    46.9 2490.31    59.5 2484.76
    69.8 2477.56      89 2461.75   101.6  2455.2   111.4 2454.31   139.5 2456.21
   168.9  2455.9   198.4 2457.36   206.8 2453.84     2122453.724   219.4 2452.92
   226.12453.592   244.6 2455.69   279.3 2454.83   291.2 2456.14   312.4 2461.35
   333.5 2476.05   388.5  2502.3     397  2505.3   422.4 2516.17   435.1 2520.58
   460.5    2533   502.6 2552.26   515.5 2557.04   557.8 2575.01   584.9    2585
#Mann= 3 ,-1,0
       0      .1       0     212    .045       0   226.1      .1       0
#XS Ineff= 2 , 0
          195.43 2459.42  263.86          2461.1
Permanent Ineff=
       F       F
Bank Sta=212,226.1
XS Rating Curve= 0 ,0
Exp/Cntr(USF)=0,0
Exp/Cntr=0.3,0.1

Type RM Length L Ch R = 1 ,8843    ,226,223,215
BEGIN DESCRIPTION:
Structure XS 4
END DESCRIPTION:
XS GIS Cut Line= 4
2313225.57446148677916.5989513282313405.68504474 678042.05393336
2313477.87940984678294.9355017962313662.65502788678499.459512657
#Sta/Elev= 30
       0 2527.86    36.8 2515.47    61.7 2503.47    71.2 2497.65    81.2 2495.75
    90.9 2489.25   120.2 2487.81     183 2475.98     203 2469.94   247.7  2465.7
   298.5 2457.41   310.1 2453.67   318.4 2445.12   322.6 2441.89   335.1 2440.61
  342.57 2441.94     360 2446.23   372.5 2444.37   418.3    2446     457 2445.31
   472.3 2446.05   496.3 2460.01   517.8  2465.4   550.2 2477.62   604.1 2508.25
   647.2 2530.57   688.8 2548.48   700.7 2556.55   733.5  2570.8   758.1 2576.08
#Mann= 8 ,-1,0
       0      .1       0      20     .06       0      90      .1       0
     140     .06       0   322.6    .045       0  342.57      .1       0
   349.5     .06       0   449.5      .1       0
Bank Sta=322.6,342.57
XS Rating Curve= 0 ,0
Exp/Cntr(USF)=0,0
Exp/Cntr=0.3,0.1

Type RM Length L Ch R = 1 ,8620    ,69.8,68.9,69.6
BEGIN DESCRIPTION:
Structure XS 3
END DESCRIPTION:
XS GIS Cut Line= 6
2313092.69151024678044.4621486812313323.14053095678139.318741633
2313320.20932409678333.4870855672313370.72908266678402.370446766
2313429.55703485678572.7297268622313671.60486499678539.836107942
#Sta/Elev= 30
       0 2532.58    33.9 2520.96    64.9 2515.81    81.6 2509.56   101.3 2508.64
   107.6 2506.64   119.7 2499.26   137.9  2498.1   163.8 2485.98   185.4 2477.65
   237.3 2461.44   291.1 2456.63   295.1 2455.54   308.8 2447.33   319.1 2444.11
   375.1 2438.91   435.1 2436.34  445.582432.371   454.3 2431.04     463 2432.39
   471.5 2434.11     486 2439.76   588.2  2435.8   667.5 2443.75   710.1 2444.15
     745 2467.81   825.8 2512.07   870.2 2539.08   922.6 2567.36   954.4 2580.71
#Mann= 9 ,-1,0
       0      .1       0     160     .06       0  279.21      .1       0
  379.21     .06       0  445.58    .045       0     463     .06       0
  485.62      .1       0  589.73     .06       0  720.08      .1       0
Bank Sta=445.58,463
XS Rating Curve= 0 ,0
Exp/Cntr(USF)=0,0
Exp/Cntr=0.3,0.1

Type RM Length L Ch R = 1 ,8551    ,316.9,311.4,305.2
BEGIN DESCRIPTION:
Structure XS 2
END DESCRIPTION:
XS GIS Cut Line= 6
 2313071.4402605678082.5678378552313286.88396468678166.107233351
2313280.70225614678364.2664553852313321.22373778678422.219102071
2313389.47620476678618.9786931492313679.66568386678579.407400545
#Sta/Elev= 30
       0 2535.84    13.7 2530.97    29.4 2527.74      48 2518.67    73.7 2513.62
   104.6    2500   129.3 2496.52   141.7 2490.45   231.1 2461.85   266.1 2460.54
   300.2 2455.64   342.2 2447.84   372.9 2439.11   454.3 2434.64472.57782429.928
   480.2 2429.25488.15462430.046   501.5  2433.6   571.4 2431.26   627.4 2432.09
   728.8 2429.57   745.9 2431.35   761.1  2439.5   777.2 2451.34   785.3 2454.96
   809.8  2472.7   837.8 2485.81   890.3 2513.83   922.6 2535.37  1002.8 2583.12
#Mann= 7 ,-1,0
       0      .1       0     180     .06       0     230      .1       0
  331.07     .06       0472.5778    .045       0488.1546     .06       0
  759.91      .1       0
#XS Ineff= 2 , 0
                          504.26         2481.76
Permanent Ineff=
       F       F
Bank Sta=472.5778,488.1546
XS Rating Curve= 0 ,0
Exp/Cntr(USF)=0,0
Exp/Cntr=0.3,0.1

Type RM Length L Ch R = 1 ,8240    ,248.7,252.5,259
BEGIN DESCRIPTION:
Structure XS 1
END DESCRIPTION:
XS GIS Cut Line= 3
2313058.99889078678720.4922668012313444.94112728678715.606922035
2313641.98336617678674.895715653
#Sta/Elev= 30
       0 2473.23    41.2 2466.71    53.2 2466.54   105.2 2461.65   165.2 2458.46
   181.2 2455.62   201.2 2447.58   205.2 2445.26   213.2  2439.6   229.2 2425.57
   233.2 2423.15   240.9 2420.21   245.2  2419.5   261.2 2419.34  263.372420.344
   269.2 2423.75   273.2 2424.53   309.2 2423.01   333.2 2427.31   377.2 2427.39
   389.3 2433.71   421.2 2452.66   479.7  2480.2   507.7 2494.62   543.1 2515.67
   556.9 2524.76   560.8 2527.55   564.9 2531.94   576.9 2542.59   587.2 2549.75
#Mann= 5 ,-1,0
       0      .1       0   240.9    .045       0  263.37      .1       0
     280     .06       0     380      .1       0
Bank Sta=240.9,263.37
XS Rating Curve= 0 ,0
Exp/Cntr(USF)=0,0
Exp/Cntr=0.3,0.1

Type RM Length L Ch R = 1 ,7987    ,296.8,300.1,302.4
XS GIS Cut Line= 3
2313023.17302916678845.8827824592313407.48681741679038.039676583
2313531.24888481679173.200881773
#Sta/Elev= 30
       0  2481.1      19 2478.39    50.3 2471.72    77.1 2464.16    86.1 2460.62
      95 2459.79   143.3 2439.58   162.1  2433.2   185.1 2418.26     197 2413.09
   211.9 2413.74   238.1 2413.09   247.1 2412.16   254.3  2409.5   269.4 2408.21
   275.7  2409.5   287.3 2414.83   301.3 2417.95   323.1 2417.15   372.3 2420.15
   381.3 2418.26   393.8 2418.09   403.6 2421.25   421.5 2421.87   442.5 2432.01
     455 2435.51   517.3 2442.83   531.6 2446.09   571.1    2460   612.9 2478.91
#Mann= 5 ,-1,0
       0      .1       0   254.3    .045       0   275.7      .1       0
     350     .06       0  469.68      .1       0
Bank Sta=254.3,275.7
XS Rating Curve= 0 ,0
Exp/Cntr(USF)=0,0
Exp/Cntr=0.3,0.1

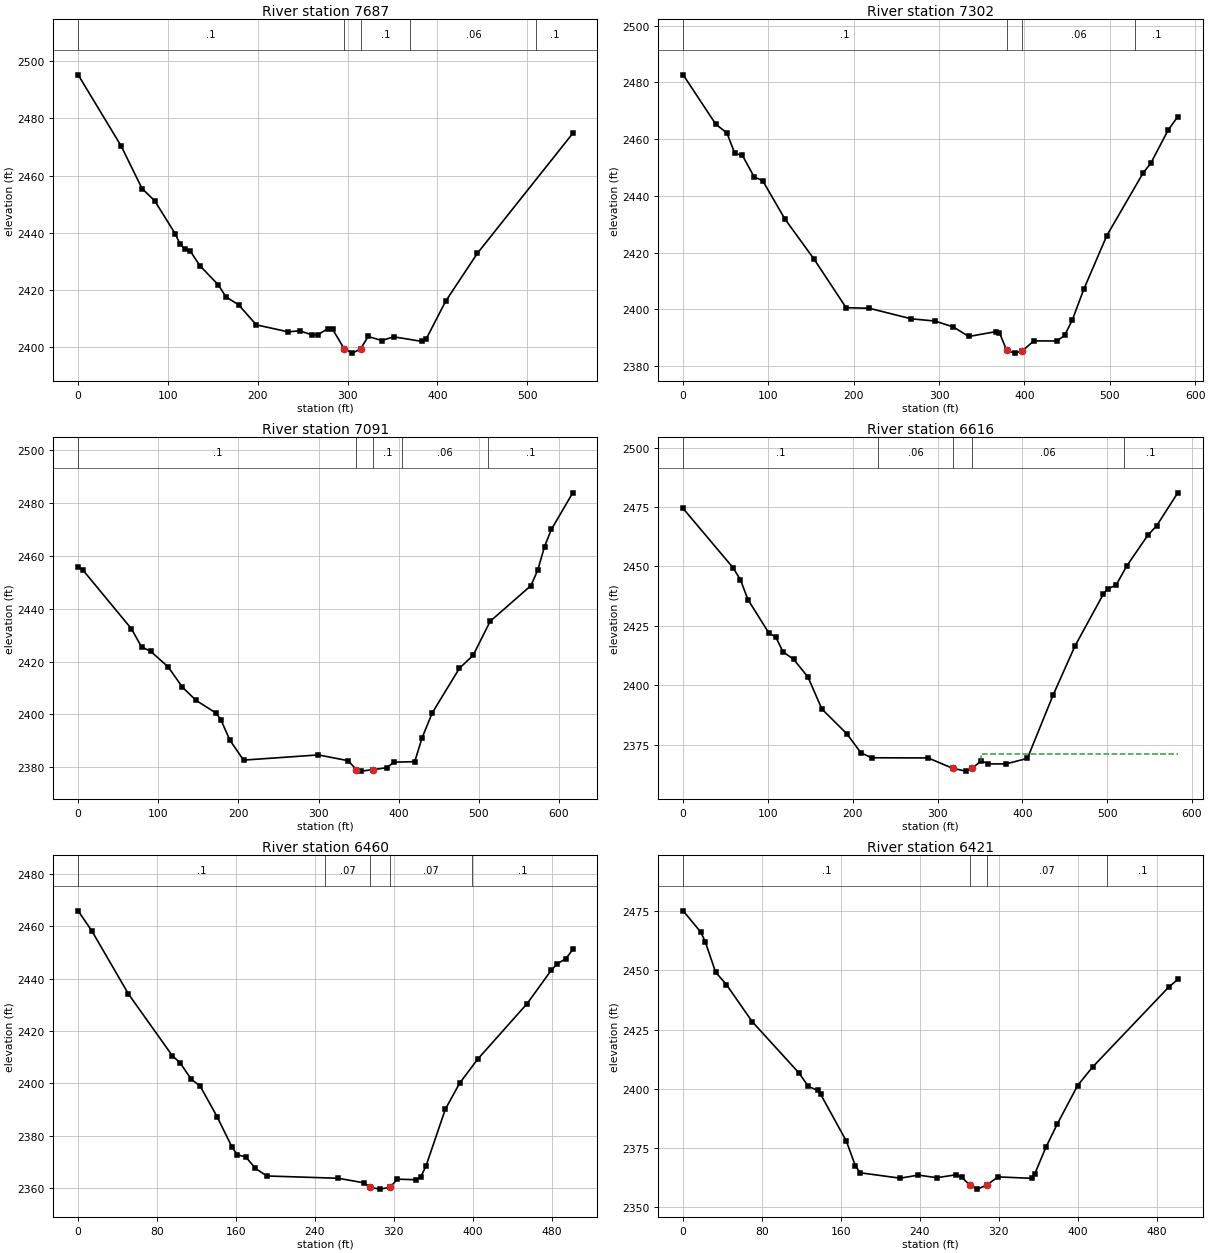
Type RM Length L Ch R = 1 ,7687    ,387.4,385.3,382.9
XS GIS Cut Line= 2
 2312865.2135484678995.7000219462313267.44026745679371.871568919
#Sta/Elev= 30
       0 2495.16    47.9 2470.31    71.1 2455.47    85.2  2451.2   107.9 2439.77
   113.5 2436.05   119.1 2434.26   124.8 2433.68   135.5 2428.55     156 2421.86
   164.5 2417.65   178.6 2414.89   198.4 2407.87   234.1 2405.43   246.5 2405.82
   260.7 2404.34   266.9 2404.48   277.9  2406.5   283.3 2406.35  296.112399.583
   305.3 2398.01   314.4 2399.47   322.9 2403.82   338.1  2402.4   351.2 2403.71
   382.8  2402.1   387.4  2402.9   409.3  2416.2   444.6 2432.89   550.7 2474.73
#Mann= 5 ,-1,0
       0      .1       0  296.11    .045       0   314.4      .1       0
     370     .06       0     510      .1       0
Bank Sta=296.11,314.4
XS Rating Curve= 0 ,0
Exp/Cntr(USF)=0,0
Exp/Cntr=0.3,0.1

Type RM Length L Ch R = 1 ,7302    ,205.7,210.4,214.5
XS GIS Cut Line= 2
2312502.06958746679301.8482939412313018.28768439679565.656911299
#Sta/Elev= 30
       0 2482.65    38.3 2465.22    51.3 2462.19    60.5 2454.96    69.4 2454.28
    83.2 2446.71    93.2 2445.35   119.2 2431.88   153.4 2417.72     191  2400.6
   218.1 2400.41   267.4 2396.68   295.4  2395.9   316.8 2393.78   334.8 2390.46
   366.7 2392.19   370.7  2391.8  379.122385.604   388.7  2384.6   397.7 2385.46
   411.1 2388.92   438.1 2388.87   447.1 2390.85   456.1 2396.28   469.5 2407.07
   496.5 2425.99   539.1 2448.07   548.1 2451.52   568.4 2463.18   579.7 2467.91
#Mann= 4 ,-1,0
       0      .1       0  379.12    .045       0   397.7     .06       0
     530      .1       0
Bank Sta=379.12,397.7
XS Rating Curve= 0 ,0
Exp/Cntr(USF)=0,0
Exp/Cntr=0.3,0.1

Type RM Length L Ch R = 1 ,7091    ,479.1,475,466.3
XS GIS Cut Line= 5
2312405.48795611679500.5290184442312695.36515328679602.570369893
2312701.04436894679617.8494639752312761.29666496679695.490006509
2312945.31980742679761.256573036
#Sta/Elev= 30
       0 2455.79     5.8 2454.72    66.5 2432.42    79.2 2425.52    90.4 2423.92
   112.4 2417.96   130.1 2410.31     147 2405.33   172.5  2400.4   178.3 2397.84
   189.4 2390.21   206.4 2382.66   299.7 2384.63   336.8 2382.46  347.23 2379.09
   353.1 2378.49   368.3 2379.07   385.2 2379.78     394 2381.88   420.1 2382.08
   429.2 2391.08   441.9 2400.53   475.9 2417.49   492.9 2422.32   514.2 2435.25
   565.1 2448.78   573.6 2454.64   582.1 2463.58   590.6 2470.08   617.3 2483.93
#Mann= 5 ,-1,0
       0      .1       0  347.23    .045       0   368.3      .1       0
  403.61     .06       0  511.89      .1       0
Bank Sta=347.23,368.3
XS Rating Curve= 0 ,0
Exp/Cntr(USF)=0,0
Exp/Cntr=0.3,0.1

Type RM Length L Ch R = 1 ,6616    ,149.6,156,161.6
XS GIS Cut Line= 2
2312251.44696181679966.7503365062312810.00471337680134.480506801
#Sta/Elev= 30
       0 2474.42    59.2 2449.31    67.6 2444.36    76.4 2436.04     101 2422.03
   109.3 2420.22   117.7 2414.04   130.2 2410.94   147.1 2403.47   163.6 2389.96
   192.9 2379.58   209.6 2371.55   222.1 2369.45   288.9 2369.37  317.73 2365.01
   333.4 2363.82   340.82365.046   351.6 2368.15   359.9 2366.84   380.8 2366.88
   405.9 2369.19   436.1 2395.77   461.8 2416.36   495.2 2438.21   500.4  2440.6
   510.3 2442.06     523  2450.2   547.9 2463.17   558.2 2467.11   583.2 2481.02
#Mann= 5 ,-1,0
       0      .1       0     230     .06       0  317.73    .045       0
   340.8     .06       0     520      .1       0
#XS Ineff= 2 , 0
                          350.96         2371.11
Permanent Ineff=
       F       F
Bank Sta=317.73,340.8
XS Rating Curve= 0 ,0
Exp/Cntr(USF)=0,0
Exp/Cntr=0.3,0.1

Type RM Length L Ch R = 1 ,6460    ,39.4,39.7,40.2
XS GIS Cut Line= 4
2312253.10235849679997.577555532 2312413.0374232680100.386917313
2312521.56780702680230.7499375622312642.73716553680304.146746318
#Sta/Elev= 30
       0 2465.98    14.1 2458.16      51 2434.15    95.4 2410.58   103.5 2407.74
   114.8 2401.46   123.5 2399.03   140.9 2387.17   155.8 2375.69   161.1 2372.69
   170.1 2371.75   179.6 2367.47   191.2 2364.53   263.8 2363.64   289.5 2361.91
   296.2 2360.14   305.7 2359.49   316.1 2360.17   323.6 2363.31   342.1 2363.08
   347.3 2364.15   352.5 2368.21   372.2 2390.03   386.7 2400.02   404.9 2409.16
   455.2  2430.5   479.7 2443.29   485.7 2445.75   494.5 2447.67   501.4 2451.19
#Mann= 5 ,-1,0
       0      .1       0  250.13     .07       0   296.2    .045       0
   316.1     .07       0  399.76      .1       0
Bank Sta=296.2,316.1
XS Rating Curve= 0 ,0
Exp/Cntr(USF)=0,0
Exp/Cntr=0.3,0.1

Type RM Length L Ch R = 1 ,6421    ,162.4,161.3,156.3
XS GIS Cut Line= 4
2312221.36518055680019.3981928622312381.30024526680122.207554643
2312489.83062908680252.5705748922312610.99998759680325.967383648
#Sta/Elev= 30
       0 2475.09    18.1 2465.97    22.4 2462.04    32.9 2449.21    43.8    2444
    69.9 2428.38   117.5 2406.63     127 2400.98   136.5 2399.31   139.4 2397.66
   165.4 2377.96   174.5  2367.6   179.3 2364.57     220 2362.29   238.4 2363.59
   257.1 2362.49   276.6 2363.72   282.5 2362.66   290.8 2359.27   298.1 2357.67
  307.51 2359.32   319.2 2362.83   353.3 2362.23   356.2 2363.86   367.7 2375.32
   379.4 2385.26   399.9 2401.39     415 2409.16   492.2  2442.9   501.4 2446.13
#Mann= 4 ,-1,0
       0      .1       0   290.8    .045       0  307.51     .07       0
  429.76      .1       0
Bank Sta=290.8,307.51
XS Rating Curve= 0 ,0
Exp/Cntr(USF)=0,0
Exp/Cntr=0.3,0.1

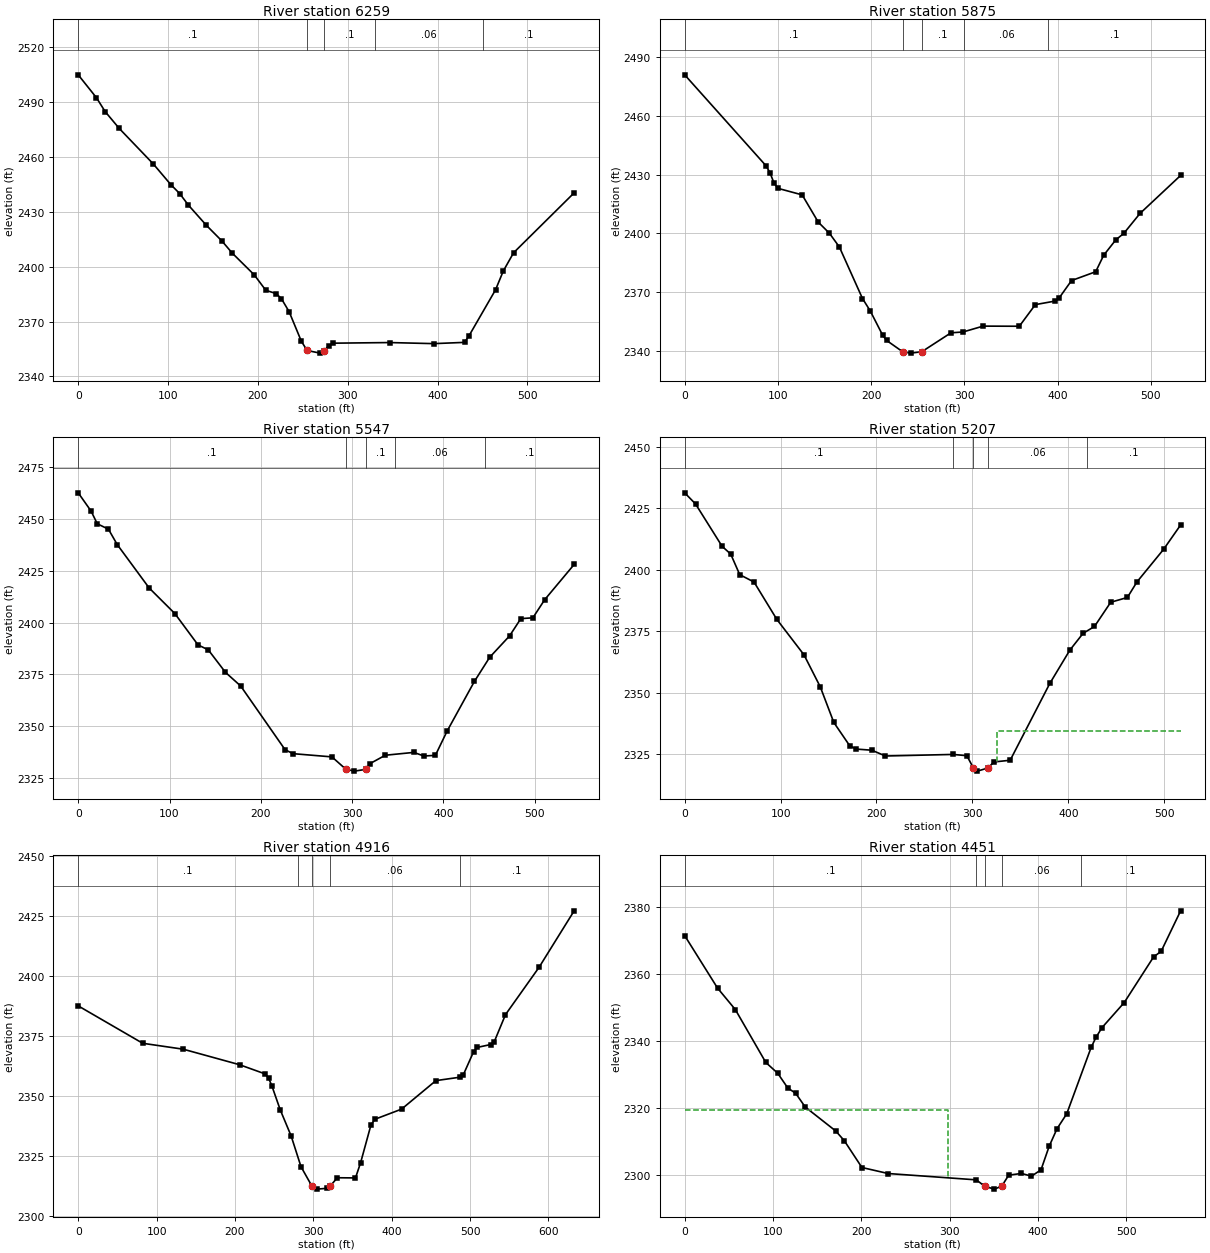
Type RM Length L Ch R = 1 ,6259    ,386.6,384.6,381.9
XS GIS Cut Line= 2
2312083.55838585680103.0448355472312536.26700083680418.963797074
#Sta/Elev= 30
       0 2504.92    20.3  2492.4      30 2484.81    45.7 2475.58    83.7 2456.11
   103.2 2444.82   112.9 2440.01   122.6 2433.69   142.7  2422.6     160 2414.04
   171.4 2407.45   195.9 2395.55   208.8  2387.1   220.4 2385.28   226.1 2382.56
   234.7 2375.45   248.4 2359.19   254.8 2354.18   269.2 2352.74   273.9 2354.16
   278.8 2356.74   283.7 2358.18   346.7 2358.52   395.8 2357.93     430 2358.62
   434.9 2362.16   464.5 2387.36   473.1 2397.62   484.6 2407.63     552 2440.39
#Mann= 5 ,-1,0
       0      .1       0   254.8    .045       0   273.9      .1       0
     330     .06       0     450      .1       0
Bank Sta=254.8,273.9
XS Rating Curve= 0 ,0
Exp/Cntr(USF)=0,0
Exp/Cntr=0.3,0.1

Type RM Length L Ch R = 1 ,5875    ,328.9,328.3,327.9
XS GIS Cut Line= 2
2311883.25925045 680479.216382522312376.67907181680677.887069667
#Sta/Elev= 30
       0 2481.11    87.2  2434.6    91.4 2431.09    95.9 2425.64   100.2 2423.01
     126 2419.69   143.3 2405.72   155.2 2400.08   165.9 2393.04   190.7 2366.67
     199 2360.34   212.3 2347.94   216.6 2345.21   233.8 2339.43   242.5 2338.73
   254.3 2339.44   285.6 2349.12   298.5 2349.55   320.1 2352.55   358.9 2352.48
   376.1 2363.55   397.7  2365.4   401.9 2367.14   414.9 2375.85   440.8 2380.37
   449.4 2388.81   462.4 2396.69     471 2400.01   488.3 2410.17   531.9 2429.64
#Mann= 5 ,-1,0
       0      .1       0   233.8    .045       0   254.3      .1       0
     300     .06       0     390      .1       0
Bank Sta=233.8,254.3
XS Rating Curve= 0 ,0
Exp/Cntr(USF)=0,0
Exp/Cntr=0.3,0.1

Type RM Length L Ch R = 1 ,5547    ,334.8,339.7,343.9
XS GIS Cut Line= 4
 2311790.4376999 680697.428448732311948.39718066 680860.27327426
2312107.98510968680914.0120666842312246.40321138680966.122410854
#Sta/Elev= 30
       0 2462.49      14 2453.76    20.9 2447.57    33.1 2444.98    42.7 2437.58
    77.7 2416.65   105.9  2404.3   131.2 2389.24   142.5 2386.82   161.3    2376
     178  2369.4   226.5 2338.79   235.1 2336.84   277.9 2335.28   293.22329.311
   302.6 2328.42   315.3 2329.29   319.5 2332.02   336.4 2336.08   367.6 2337.44
   378.6 2335.71   391.2 2336.01     404 2347.67   433.9  2371.6   450.7 2383.27
   472.4 2393.53   484.8 2401.88     498 2402.28   510.9 2410.99   543.2 2427.98
#Mann= 5 ,-1,0
       0      .1       0   293.2    .045       0   315.3      .1       0
  346.87     .06       0  445.26      .1       0
Bank Sta=293.2,315.3
XS Rating Curve= 0 ,0
Exp/Cntr(USF)=0,0
Exp/Cntr=0.3,0.1

Type RM Length L Ch R = 1 ,5207    ,299.8,291.1,286.3
XS GIS Cut Line= 2
2311608.05149531680925.4112044722311980.96614577681283.669820637
#Sta/Elev= 30
       0 2431.34    11.3 2426.82      39 2409.57      48  2406.4    57.4 2398.02
    72.3 2395.02    96.1  2379.8   124.4 2365.38   141.4 2352.33   155.5 2337.85
   172.1 2328.35   178.7 2327.01   195.1 2326.55   209.3 2324.19     280 2324.83
   294.2 2324.31  300.932319.386   305.2 2318.03   316.3 2319.32   322.4 2321.76
   339.4 2322.46   380.7 2353.72   401.6 2367.29   415.4 2374.13   427.3 2376.93
   444.2 2386.78   461.6 2388.74   471.6 2395.08   499.4 2408.36   517.1 2418.25
#Mann= 5 ,-1,0
       0      .1       0     280     .06       0  300.93    .045       0
   316.3     .06       0     420      .1       0
#XS Ineff= 2 , 0
                          325.68         2334.37
Permanent Ineff=
       F       F
Bank Sta=300.93,316.3
XS Rating Curve= 0 ,0
Exp/Cntr(USF)=0,0
Exp/Cntr=0.3,0.1

Type RM Length L Ch R = 1 ,4916    ,460.7,464.8,468.1
XS GIS Cut Line= 3
2311300.27477506681241.3301659992311686.21701156681335.780164806
2311901.17218126681431.858611869
#Sta/Elev= 30
       0 2387.59    82.3 2371.97     134  2369.5   205.8 2363.03   238.7 2359.16
   242.9 2357.42     247 2354.28   257.8 2344.16   271.7 2333.27   284.3 2320.41
  298.012312.448   304.6 2311.08     317 2311.41   321.8 2312.47   330.6 2315.83
   353.8 2315.76   360.4 2322.19   373.6 2337.96   378.8 2340.28   412.6 2344.48
   456.4 2356.38   487.7 2357.84   491.5  2358.9   504.6 2368.53     509 2370.24
   526.5 2371.46   530.9 2372.65   545.2 2383.94   587.9 2403.63   632.8 2427.27
#Mann= 5 ,-1,0
       0      .1       0     280     .06       0  298.01    .045       0
   321.8     .06       0  487.33      .1       0
Bank Sta=298.01,321.8
XS Rating Curve= 0 ,0
Exp/Cntr(USF)=0,0
Exp/Cntr=0.3,0.1

Type RM Length L Ch R = 1 ,4451    ,344.6,345.9,350.3
XS GIS Cut Line= 3
2311205.82477625681539.3361967182311544.54201335681785.231883268
2311681.33166679 681825.94308965
#Sta/Elev= 30
       0 2371.56    37.2 2355.88    57.3 2349.47    91.8 2333.67   105.3 2330.44
   116.6 2326.07   125.7 2324.42   136.4 2320.36     171 2313.18   180.6 2310.31
   200.6 2302.28   230.3 2300.48     330 2298.59  339.662296.674   350.4 2295.82
   358.8 2296.68   366.7 2299.98   381.1 2300.51   392.5 2299.69   403.3 2301.59
   412.5 2308.61   421.4 2313.86   432.4 2318.32     460 2338.14   465.6 2341.21
   472.4 2344.09   497.5 2351.56   530.8 2365.23   539.2 2366.83   561.3 2378.96
#Mann= 5 ,-1,0
       0      .1       0     330     .06       0  339.66    .045       0
   358.8     .06       0  448.56      .1       0
#XS Ineff= 2 , 0
          297.62 2319.31
Permanent Ineff=
       F       F
Bank Sta=339.66,358.8
XS Rating Curve= 0 ,0
Exp/Cntr(USF)=0,0
Exp/Cntr=0.3,0.1