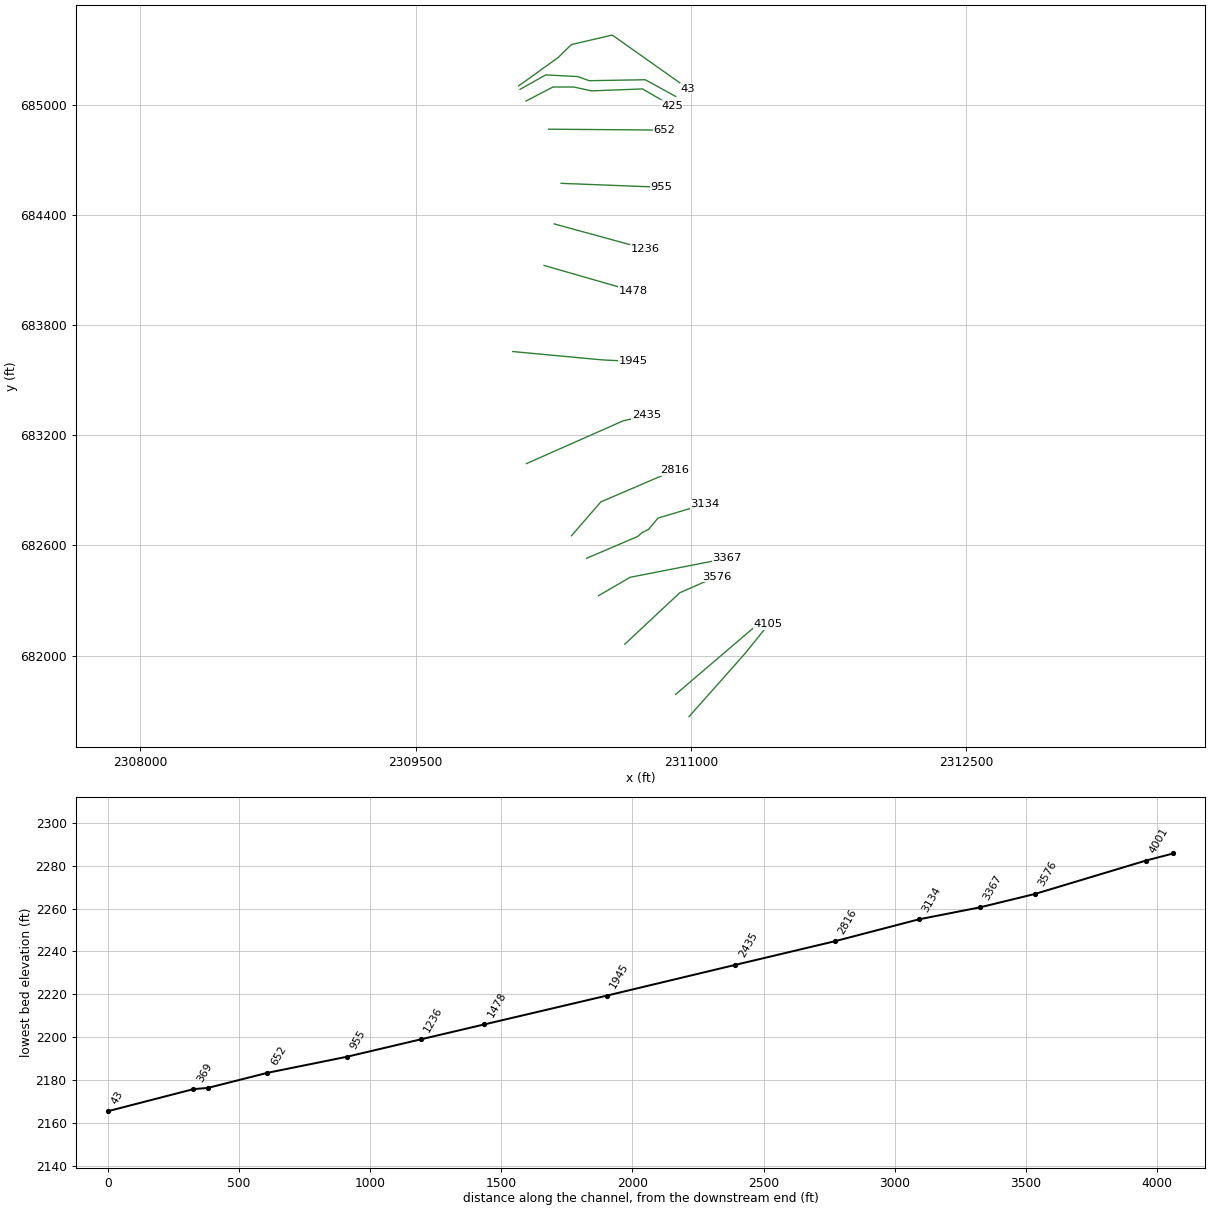
HEC-RAS study RFKCHENOCK.prj: RFKCHENOCK

--- RFKCHENOCK.g01 (geometry) --- (continued)

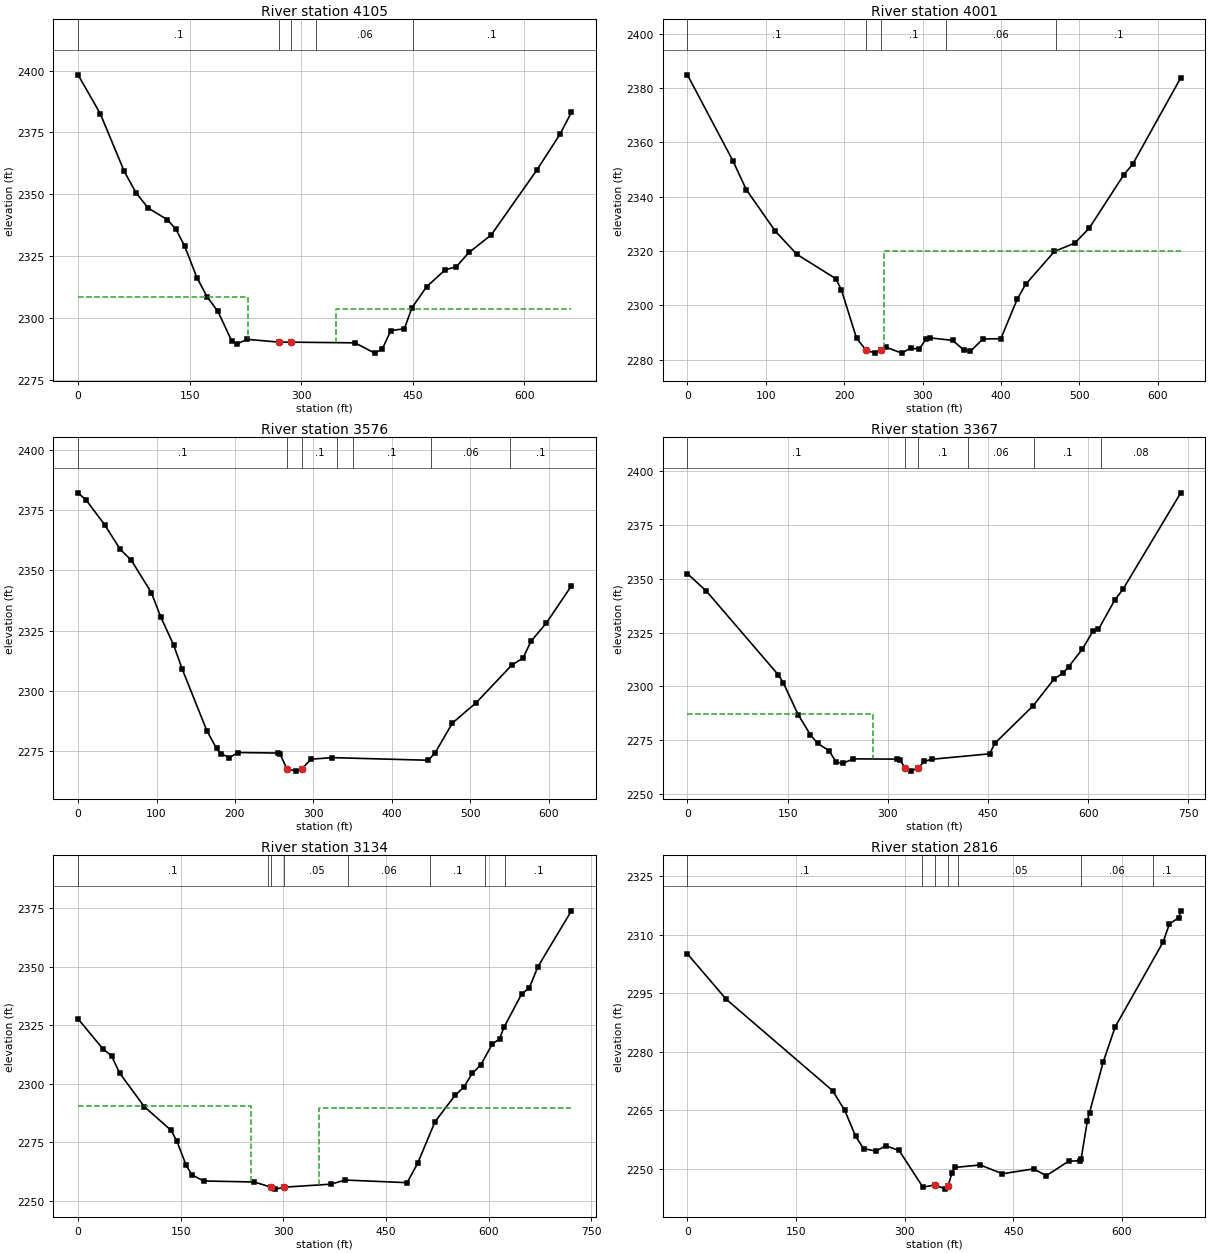
Type RM Length L Ch R = 1 ,4105    ,104.5,104.1,102.2
BEGIN DESCRIPTION:
Disconnected without IFA
END DESCRIPTION:
XS GIS Cut Line= 3
2310989.05427172681666.7831365172311292.63297311682009.016268831
2311421.79533985 682169.29073851
#Sta/Elev= 30
       0 2398.31    29.9 2382.54      62 2359.28    78.1  2350.5    94.1 2344.42
   120.1 2339.67   131.5 2335.85   143.3    2329   159.7 2316.26   173.5 2308.46
   188.1 2302.53   206.4 2290.69   213.6 2289.44   227.7 2291.25   270.5 2290.12
  286.55 2290.12   372.3 2289.84   398.9 2285.68   409.1 2287.37   420.4 2294.79
   438.7 2295.54   448.8    2304   468.6 2312.55   493.6  2319.4   508.5 2320.64
   525.5 2326.41   555.3 2333.46   616.6 2359.69   647.9 2374.26   663.3 2383.15
#Mann= 5 ,-1,0
       0      .1       0   270.5    .045       0  286.55      .1       0
     320     .06       0     450      .1       0
#XS Ineff= 2 , 0
             229 2308.36  346.96         2303.48
Permanent Ineff=
       F       F
Bank Sta=270.5,286.55
XS Rating Curve= 0 ,0
Exp/Cntr(USF)=0,0
Exp/Cntr=0.3,0.1

Type RM Length L Ch R = 1 ,4001    ,424,424.6,424.5
BEGIN DESCRIPTION:
Disconnected without IFA
END DESCRIPTION:
XS GIS Cut Line= 2
2310916.16727325 681788.345983912311394.67460735682197.020831764
#Sta/Elev= 30
       0 2384.85    57.9 2353.28    75.2 2342.52   112.1  2327.3   139.6 2318.76
   189.4 2309.76   196.4 2305.69   215.7  2287.9   227.82283.472   238.9 2282.43
  246.37 2283.48   253.8 2284.49   273.5 2282.37   284.6 2284.21   295.7 2283.83
   304.2 2287.47   309.2 2287.99   338.2 2287.08   352.4 2283.59   360.9 2283.01
     377 2287.59   399.8 2287.68   420.8 2302.31   431.4 2307.68   468.2 2319.83
     494 2322.87   512.5 2328.35   556.7 2348.07   567.9 2351.88   629.3 2383.76
#Mann= 5 ,-1,0
       0      .1       0   227.8    .045       0  246.37      .1       0
     330     .06       0     470      .1       0
#XS Ineff= 2 , 0
                           251.2         2319.91
Permanent Ineff=
       F       F
Bank Sta=227.8,246.37
XS Rating Curve= 0 ,0
Exp/Cntr(USF)=0,0
Exp/Cntr=0.3,0.1

Type RM Length L Ch R = 1 ,3576    ,212.8,209.3,201.8
XS GIS Cut Line= 3
2310639.26121462682061.9846377742310938.89569359682342.077737685
2311139.19482899682430.013943471
#Sta/Elev= 30
       0 2382.15    10.5 2379.06      34 2368.85    53.8 2358.69      68 2354.13
    93.5 2340.71   105.3 2330.76   121.8 2319.05   132.7  2309.1   164.2 2283.47
   176.5 2276.16   181.9 2274.03   192.9 2272.34   203.8 2274.47   254.8 2274.26
   257.6 2273.69   266.1 2267.82   277.4 2266.76  285.452267.818   297.2 2271.73
   324.3 2272.35   446.5 2271.27   455.2  2274.4   477.2  2286.7   507.7  2295.2
   553.1 2310.79   567.1 2313.58   577.4 2320.63     597 2328.21   628.9 2343.57
#Mann= 7 ,-1,0
       0      .1       0   266.1    .045       0  285.45      .1       0
     330     .06       0     350      .1       0  450.16     .06       0
  550.16      .1       0
Bank Sta=266.1,285.45
XS Rating Curve= 0 ,0
Exp/Cntr(USF)=0,0
Exp/Cntr=0.3,0.1

Type RM Length L Ch R = 1 ,3367    ,231.9,233.3,234.7
XS GIS Cut Line= 3
2310495.59433677682325.666339997 2310668.1149898682426.243344085
2311197.08514539682529.601132338
#Sta/Elev= 30
       0 2352.41    28.5 2344.27   136.2  2305.3   143.4 2301.76   165.8 2286.84
   184.3 2277.38   195.1 2273.41     212 2270.09   222.7 2264.74   232.4 2264.17
   248.7 2266.25   313.9 2266.12     318  2265.8   326.1 2262.01   334.3 2260.54
   345.62261.944   354.6 2265.11   366.9 2266.08   452.4 2268.59   460.6 2273.56
   517.7 2290.94   548.7 2303.27   562.5 2306.14   570.9 2309.16   591.2 2317.19
   607.3 2325.66   615.5 2326.49   639.9 2340.13   652.2 2345.13   738.7 2390.01
#Mann= 6 ,-1,0
       0      .1       0   326.1    .045       0   345.6      .1       0
   419.7     .06       0   519.7      .1       0   619.7     .08       0
#XS Ineff= 2 , 0
          278.41 2287.28
Permanent Ineff=
       F       F
Bank Sta=326.1,345.6
XS Rating Curve= 0 ,0
Exp/Cntr(USF)=0,0
Exp/Cntr=0.3,0.1

Type RM Length L Ch R = 1 ,3134    ,313.7,317.7,316.5
XS GIS Cut Line= 6
2310430.94715133682529.7333591042310709.78681866682648.902267209
2310732.37438948682669.1531927692310768.98183183682687.846354825
2310819.60914574682748.599131506 2311075.0823605682824.929543233
#Sta/Elev= 30
       0 2327.75      36 2315.03      49 2311.89    60.6 2304.62    96.8 2290.19
   135.8  2280.1   144.5 2275.35   157.5 2265.39   166.2 2261.05   183.5 2258.43
   257.3 2257.99  281.39 2255.82   288.1 2254.94   301.5 2255.78   369.3 2257.06
   390.2 2258.83   480.7  2257.7   496.4 2266.23   521.4 2283.76   550.6 2295.05
   563.2 2298.43   575.7 2304.42   588.2 2308.03   604.9 2316.91   615.7 2319.23
   622.1 2324.12   647.8  2338.3   659.2 2341.08   671.7 2350.07   720.7 2373.99
#Mann= 8 ,-1,0
       0      .1       0  277.76     .05       0  281.39    .045       0
   301.5     .05       0  394.73     .06       0  514.03      .1       0
  594.03     .06       0  624.03      .1       0
#XS Ineff= 2 , 0
             253 2290.45   351.8         2289.83
Permanent Ineff=
       F       F
Bank Sta=281.39,301.5
XS Rating Curve= 0 ,0
Exp/Cntr(USF)=0,0
Exp/Cntr=0.3,0.1

Type RM Length L Ch R = 1 ,2816    ,378.3,380.7,376.7
XS GIS Cut Line= 3
2310348.81168526682652.9190134082310508.39961428682836.933666257
2310910.62633334683009.549181318
#Sta/Elev= 30
       0  2305.1    53.6 2293.46   200.5 2270.04   217.4 2264.96   232.2 2258.39
   243.2 2255.19   260.7 2254.55   273.8 2255.92   292.3 2254.72   325.3  2245.3
   341.92245.901   356.3 2244.81     3602245.571   365.4 2249.04   369.6 2250.37
   404.4    2251   434.9 2248.75   478.1 2249.99   495.8 2248.26   526.3 2251.95
   542.1  2252.1   543.7 2252.56   552.4 2262.36   555.3 2264.41   574.1 2277.33
   590.8  2286.4   656.8 2308.07   665.6 2312.73   678.6 2314.39   681.3 2316.12
#Mann= 7 ,-1,0
       0      .1       0  323.58     .07       0   341.9    .045       0
     360     .07       0  373.58     .05       0  543.58     .06       0
  643.58      .1       0
Bank Sta=341.9,360
XS Rating Curve= 0 ,0
Exp/Cntr(USF)=0,0
Exp/Cntr=0.3,0.1

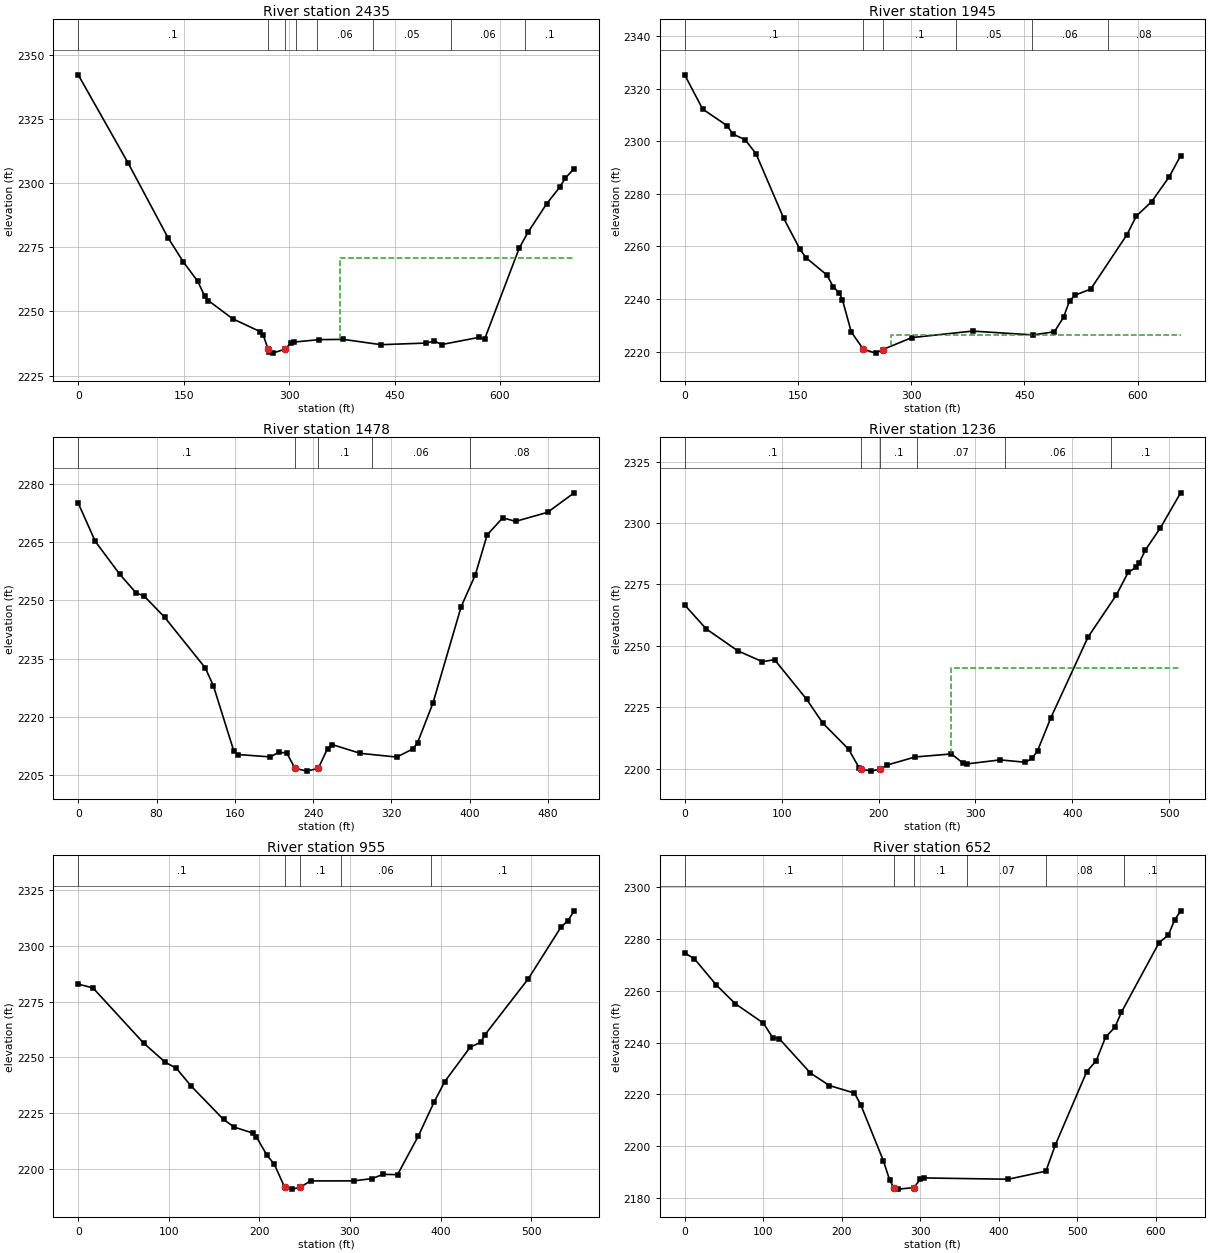
Type RM Length L Ch R = 1 ,2435    ,494.2,490.4,481.2
XS GIS Cut Line= 3
2310103.36530741683045.6508328672310629.35409387683278.518933374
2310756.37305779 683307.83100197
#Sta/Elev= 30
       0 2342.29    70.9 2307.94   127.6 2278.84   149.6 2269.32   170.1 2261.75
   180.2 2255.85   185.2 2254.24   219.6 2247.18     259 2242.13   263.4 2240.72
   270.1 2235.31   272.1 2234.17   276.5 2233.76     294 2235.28   302.7 2237.72
   306.5 2238.06   342.9 2239.02   377.1 2239.12   430.8 2237.05   495.2 2237.69
   506.6 2238.48   517.1 2237.11   569.6 2239.87   578.1 2239.14   627.4 2274.68
   639.8 2280.82   666.5 2292.02   684.9 2298.39   693.2 2302.09   705.6 2305.68
#Mann= 8 ,-1,0
       0      .1       0   270.1    .045       0     294      .1       0
     310     .05       0     340     .06       0     420     .05       0
     530     .06       0  635.23      .1       0
#XS Ineff= 2 , 0
                          372.56         2270.93
Permanent Ineff=
       F       F
Bank Sta=270.1,294
XS Rating Curve= 0 ,0
Exp/Cntr(USF)=0,0
Exp/Cntr=0.3,0.1

Type RM Length L Ch R = 1 ,1945    ,468.1,467.1,463.1
XS GIS Cut Line= 3
2310028.45668767683656.3189286032310516.99116426683610.722377455
 2310683.0928863683602.580136178
#Sta/Elev= 30
       0 2325.27    23.8 2312.24      56 2305.96      64 2302.72    80.1 2300.58
    94.5 2295.24   131.2 2270.69   152.4 2259.08   160.6 2255.75   188.5  2249.1
   196.6 2244.74   204.6 2242.37   208.9 2239.79   220.7 2227.47   236.7 2220.89
   252.8 2219.42   262.1 2220.74     301 2225.33   381.4  2227.8   461.5 2226.34
   489.8 2227.55   501.9 2233.06   509.9 2239.38   517.7 2241.53   537.9 2243.77
     586 2264.52   598.2 2271.49   618.7 2277.07     642 2286.53     657 2294.49
#Mann= 6 ,-1,0
       0      .1       0   236.7    .045       0   262.1      .1       0
     360     .05       0     460     .06       0  560.66     .08       0
#XS Ineff= 2 , 0
                          272.73         2226.28
Permanent Ineff=
       F       F
Bank Sta=236.7,262.1
XS Rating Curve= 0 ,0
Exp/Cntr(USF)=0,0
Exp/Cntr=0.3,0.1

Type RM Length L Ch R = 1 ,1478    ,241.8,242.2,243
XS GIS Cut Line= 2
2310199.44375448684125.3120261282310686.34978281683985.265476173
#Sta/Elev= 30
       0 2275.05    17.4  2265.2    42.4 2256.73      59 2251.94    67.4 2251.09
    88.2 2245.67   129.8 2232.59   138.1 2227.97   158.9 2211.21   163.1 2210.28
   196.4 2209.66   204.7 2210.86     213 2210.68   221.4 2206.75   233.4    2206
  245.212206.711   254.7  2211.8   259.3 2212.85     288 2210.59   325.4 2209.62
   342.1 2211.76   346.6 2213.31   362.3 2223.48   391.2 2248.38   405.7 2256.62
   417.7 2266.85   433.6 2271.26   446.8 2270.35   479.4 2272.67   506.6  2277.7
#Mann= 5 ,-1,0
       0      .1       0   221.4    .045       0  245.21      .1       0
     300     .06       0     400     .08       0
Bank Sta=221.4,245.21
XS Rating Curve= 0 ,0
Exp/Cntr(USF)=0,0
Exp/Cntr=0.3,0.1

Type RM Length L Ch R = 1 ,1236    ,279.2,280.2,282.8
XS GIS Cut Line= 2
2310254.81099516684351.6663336142310748.23081651684216.505128425
#Sta/Elev= 30
       0 2266.66    22.2 2256.91    54.8    2248    80.2 2243.56    92.7  2244.4
   125.8 2228.27   142.4 2218.62   169.2 2207.91   179.8 2200.48  181.832199.875
   192.2 2199.04   201.7 2199.86   208.8 2201.51   237.8 2204.81   275.1 2206.03
   287.6 2202.16   291.7    2202   325.4 2203.61   351.5 2202.64   358.3 2204.24
     364 2207.28   377.5 2220.55   416.1 2253.59   445.2 2270.64   457.6 2279.99
   465.9 2281.99   468.7 2283.64   475.2 2288.98   490.8 2298.05   511.6 2312.28
#Mann= 6 ,-1,0
       0      .1       0  181.83    .045       0   201.7      .1       0
     240     .07       0     330     .06       0     440      .1       0
#XS Ineff= 2 , 0
                          274.66         2241.07
Permanent Ineff=
       F       F
Bank Sta=181.83,201.7
XS Rating Curve= 0 ,0
Exp/Cntr(USF)=0,0
Exp/Cntr=0.3,0.1

Type RM Length L Ch R = 1 ,955     ,304.1,303.7,303.6
XS GIS Cut Line= 2
2310291.91375442 684572.826173532310838.96225596684551.548255344
#Sta/Elev= 30
       0 2282.83    16.3 2281.13    72.3 2256.37    96.3 2247.75   108.3 2245.15
   124.4 2237.27   160.4 2222.19   172.4 2218.73   192.6 2216.11   196.4 2214.53
   208.4 2206.13   216.4 2202.18227.83162191.863   236.4 2190.97244.92652191.782
   256.5 2194.65   304.5 2194.67   324.5  2195.7   336.5  2197.6   352.5 2197.45
   375.5 2214.79   392.9    2230   404.6 2239.11   432.6 2254.52   444.6 2256.86
   448.6 2259.92     497 2285.29   532.7 2308.22   540.7 2311.32   547.5 2315.67
#Mann= 5 ,-1,0
       0      .1       0227.8316    .045       0244.9265      .1       0
     290     .06       0     390      .1       0
Bank Sta=227.8316,244.9265
XS Rating Curve= 0 ,0
Exp/Cntr(USF)=0,0
Exp/Cntr=0.3,0.1

Type RM Length L Ch R = 1 ,652     ,228,226.9,226.3
BEGIN DESCRIPTION:
Structure XS 4
END DESCRIPTION:
XS GIS Cut Line= 2
2310223.87047831684867.8844305432310855.70840136684862.999085777
#Sta/Elev= 30
       0  2274.6    12.3 2272.41    40.3 2262.26    64.3 2255.08   100.3 2247.53
   112.3 2241.84   120.3  2241.6   160.3 2228.25   184.3 2223.46   216.3 2220.53
   224.3 2216.05   253.1 2194.48     261 2187.12  266.42 2184.07   272.3 2183.46
   292.3 2184.05   300.3  2187.4   304.3 2187.78   412.3 2187.28   460.3 2190.41
   472.3 2200.54   512.3 2228.84   524.3 2232.97   536.3 2242.13   548.3 2245.98
   556.3 2251.65   604.3 2278.54   616.3 2281.59   624.3 2287.33   631.9 2290.89
#Mann= 6 ,-1,0
       0      .1       0  266.42    .045       0   292.3      .1       0
     360     .07       0     460     .08       0     560      .1       0
Bank Sta=266.42,292.3
XS Rating Curve= 0 ,0
Exp/Cntr(USF)=0,0
Exp/Cntr=0.3,0.1

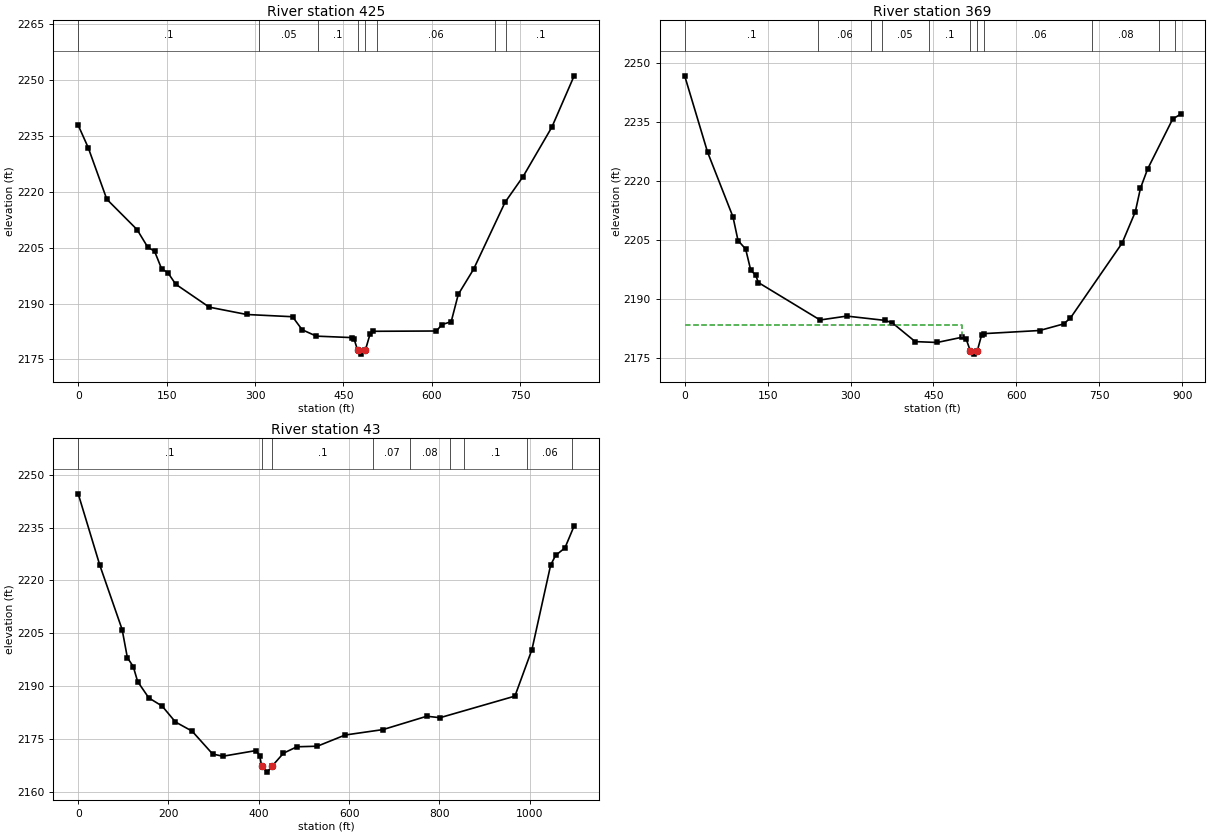
Type RM Length L Ch R = 1 ,425     ,55.6,55.4,53.7
BEGIN DESCRIPTION:
Structure XS 3
END DESCRIPTION:
XS GIS Cut Line= 6
2310101.11883068685021.5839040492310247.93972537685097.827851362
2310360.05838775685097.8278513622310457.66757617685076.723161974
2310735.98566749685087.275506668 2310895.5735965684994.128266465
#Sta/Elev= 30
       0 2237.88      17 2231.86    48.5 2218.02    99.9 2209.86   117.7 2205.22
   129.6 2204.03   141.4 2199.37   152.2 2198.28   165.4 2195.21   222.3 2189.05
   285.9 2187.08   363.6 2186.48   379.9 2182.99     404 2181.27   464.1 2180.88
   468.2 2180.42   474.1 2177.45   480.3 2176.44  487.032177.434   495.1  2181.8
   500.5 2182.57   607.8 2182.65   616.8 2184.35   632.8 2185.15   644.8 2192.48
   670.7 2199.21   724.2 2217.21   754.8 2224.12   803.6 2237.38   841.4 2251.15
#Mann= 8 ,-1,0
       0      .1       0  307.56     .05       0  407.42      .1       0
   474.1    .045       0  487.03      .1       0  506.66     .06       0
  706.58     .08       0  726.58      .1       0
Bank Sta=474.1,487.03
XS Rating Curve= 0 ,0
Exp/Cntr(USF)=0,0
Exp/Cntr=0.3,0.1

Type RM Length L Ch R = 1 ,369     ,323.6,326.3,321.6
BEGIN DESCRIPTION:
Structure XS 2
END DESCRIPTION:
XS GIS Cut Line= 6
2310067.99619316685084.9793946282310208.36843277685163.780005702
2310383.80116331685154.5467040942310444.47714531685132.122971619
2310750.49514144685137.3991439662310916.53172555685046.189757187
#Sta/Elev= 30
       0 2246.77    41.4 2227.33    87.4 2210.82    96.5 2204.81   110.3 2202.63
   119.5 2197.25   128.6 2195.95   133.2 2194.11   244.9 2184.56   293.3 2185.55
   362.6 2184.45   375.6 2183.84     417 2179.05   456.7 2178.83   501.4 2180.15
   509.4 2179.63  516.522176.775     523 2175.86   529.4 2176.73   537.4 2180.84
   541.4 2181.08   642.2 2181.88   685.4 2183.55   697.7 2185.03   791.3 2204.14
   815.2 2212.11   824.5  2218.1   837.4    2223   882.9 2235.77   897.2    2237
#Mann= 11 ,-1,0
       0      .1       0  240.98     .06       0  336.65      .1       0
  356.65     .05       0  441.34      .1       0  516.52    .045       0
   529.4      .1       0  541.96     .06       0  737.74     .08       0
  857.74     .06       0  887.74      .1       0
#XS Ineff= 2 , 0
          502.05 2183.23
Permanent Ineff=
       F       F
Bank Sta=516.52,529.4
XS Rating Curve= 0 ,0
Exp/Cntr(USF)=0,0
Exp/Cntr=0.3,0.1

Type RM Length L Ch R = 1 ,43      ,,,
BEGIN DESCRIPTION:
Structure XS 1
END DESCRIPTION:
XS GIS Cut Line= 5
2310061.15900028685104.1619675952310275.45349656 685257.98365397
2310347.63254571685328.7352867922310570.72995668685380.845630961
2310982.72736527685089.353393263
#Sta/Elev= 30
       0 2244.61      48 2224.27    97.3 2206.07   108.9 2198.08   121.9 2195.56
   131.7 2191.28   156.4 2186.65   185.9 2184.33   215.4 2179.81   252.3 2177.21
   297.7 2170.72   320.3 2170.08   394.2  2171.7     402 2170.22406.52682167.182
   418.8 2165.57429.19682167.235   454.7 2170.95   484.5 2172.77   529.7 2172.93
   591.3 2176.11   675.1 2177.65   772.1 2181.44   801.5 2181.03   967.4 2187.16
  1005.1 2200.38  1046.5 2224.36  1057.4 2227.11  1078.2 2229.25  1098.6  2235.5
#Mann= 9 ,-1,0
       0      .1       0406.5268    .045       0429.1968      .1       0
  653.96     .07       0  733.96     .08       0  823.96     .06       0
  853.96      .1       0  993.96     .06       0 1093.96     .08       0
Bank Sta=406.5268,429.1968
XS Rating Curve= 0 ,0
Exp/Cntr(USF)=0,0
Exp/Cntr=0.3,0.1
LCMann Table=0

Chan Stop Cuts=-1
Use User Specified Reach Order=0
Composite Channel Slope=5